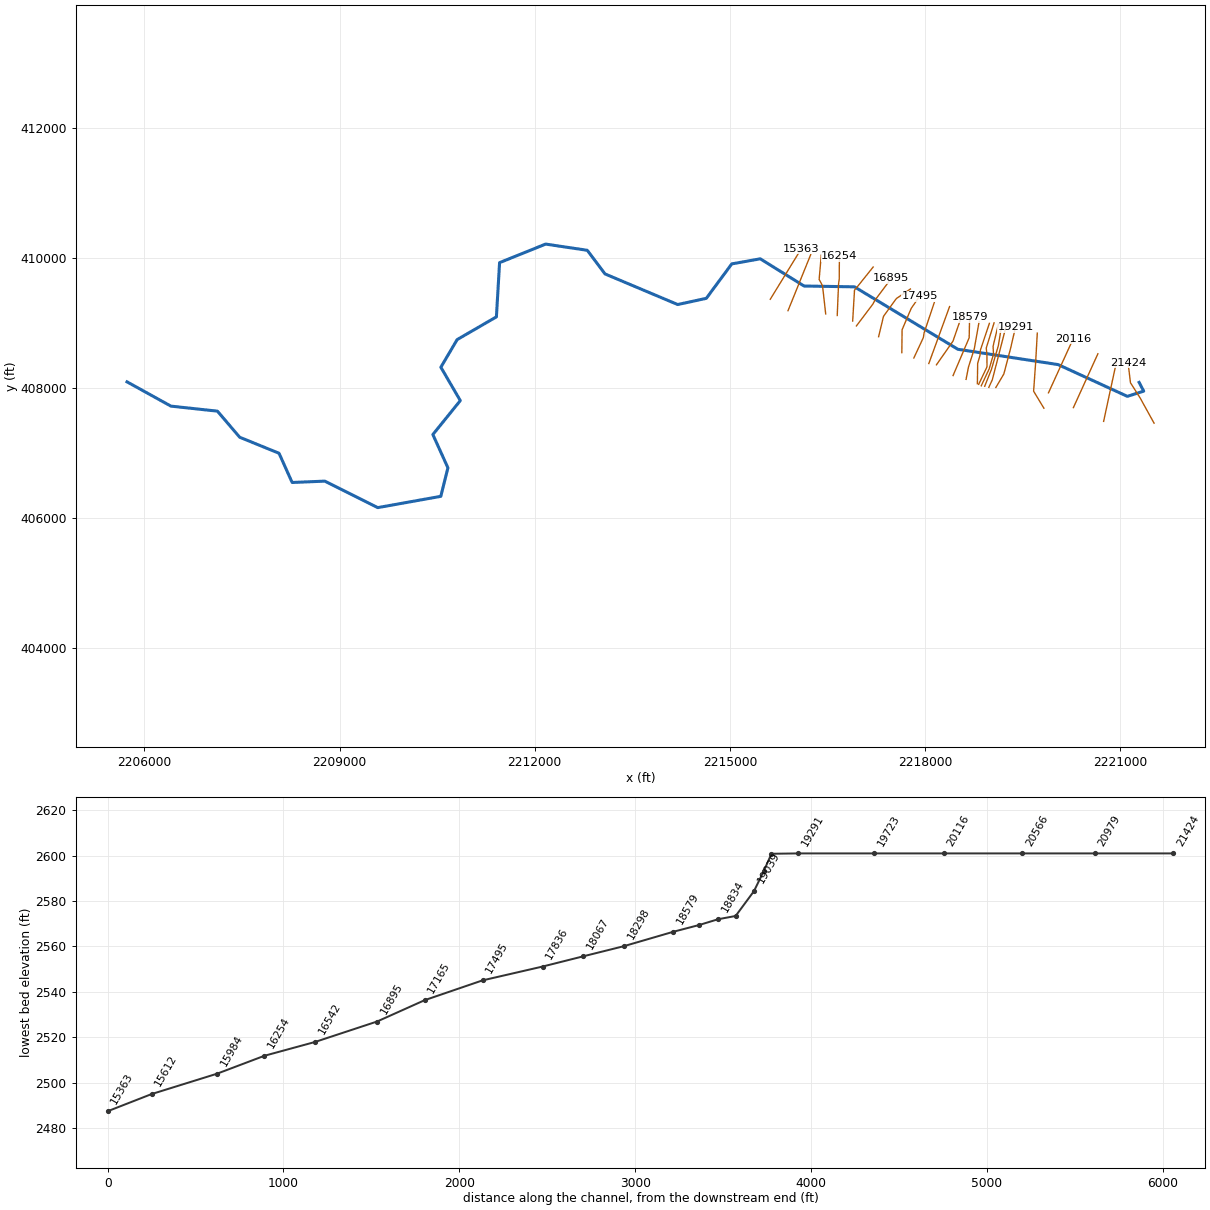
--- ISLNDLCKRN.prj (project) ---

Proj Title=ISLNDLCKRN
Current Plan=p01
Default Exp/Contr=0,0
English Units
Geom File=g01
Flow File=f01
Plan File=p01
Background Map Layer=Inundation Boundary (01pct Value_0)
Background Map Layer=Inundation Boundary (01pct Value_0)
BEGIN DESCRIPTION:
----------MODEL BY WOOD PLC 2021----------
Stream Name: Island Lick Run
Flood Zone: Enhanced Approximate
Pocahontas County, WV
HEC-RAS Version: RAS 6.1
Vertical Datum: NAVD88
Projection: NAD 1983 StatePlane West Virginia S FIPS 4702 (US Feet)
Terrain: 1-meter LIDAR (FEMA Region III 3DEP collected 2016-2018)
Land Use: 2019 NLCD
Hydrologic Method:
WV SIR2010-5033 regression equations
Model Notes:
Normal Depth tie in to Greenbrier River
END DESCRIPTION:
DSS Export Rating Curves= 0
DSS Export Rating Curve Sorted= 0
DSS Export Volume Flow Curves= 0
DXF OffsetX= 0
DXF OffsetY= 0
DXF ScaleX= 0
DXF ScaleY= 0

--- ISLNDLCKRN.p01 (plan) ---

Plan Title=Floodplain
Program Version=6.00
Short Identifier=Floodplain
Geom File=g01
Flow File=f01
Subcritical Flow
K Sum by GR= 0
Std Step Tol= 0.01
Critical Tol= 0.01
Num of Std Step Trials= 20
Max Error Tol= 0.3
Flow Tol Ratio= 0.001
Split Flow NTrial= 30
Split Flow Tol= 0.02
Split Flow Ratio= 0.02
Log Output Level= 0
Friction Slope Method= 1
Unsteady Friction Slope Method= 2
Unsteady Bridges Friction Slope Method= 1
Parabolic Critical Depth
Global Vel Dist= 0 , 0 , 0
Global Log Level= 0
CheckData=False
Encroach Param=-1 ,0,0, 0
Mapping Interval=1HOUR
Computation Time Step Use Courant=        0
Computation Time Step Use Time Series=    0
Computation Time Step Count To Double=0
Computation Time Step Max Doubling=0
Computation Time Step Max Halving=0
Computation Time Step Residence Courant=0
Run HTab= 0
Run UNet= 0
Run Sediment= 0
Run PostProcess= 0
Run WQNet= 0
Run RASMapper=-1
UNET Theta= 0
UNET Theta Warmup= 0
UNET ZTol= 0
UNET ZSATol= 0
UNET MxIter= 0
UNET Max Iter WO Improvement= 0
UNET MaxInSteps= 0
UNET DtIC= 0
UNET DtMin= 0
UNET MaxCRTS= 0
UNET WFStab= 0
UNET SFStab= 0
UNET WFX= 1
UNET SFX= 1
UNET Gravity=32.174
UNET 1D Methodology=Finite Difference
UNET DSS MLevel= 1
UNET Pardiso=0
UNET DZMax Abort= 0
UNET Use Existing IB Tables= 0
UNET Froude Reduction=False
UNET Froude Limit= 0
UNET Froude Power= 0
UNET D1 Cores= 0
UNET WindReference=Eulerian
UNET WindDragFormulation=Hsu (1988)
UNET D2 Coriolis=0
UNET D2 Cores= 0
UNET D2 Theta= 1
UNET D2 Theta Warmup= 1
UNET D2 Z Tol= 0.01
UNET D2 Volume Tol= 0.01
UNET D2 Max Iterations= 20
UNET D2 Equation= 0
UNET D2 RampUpFraction=0.1
UNET D2 TimeSlices= 1
UNET D2 Turbulence Formulation=Non-Conservative (original)
UNET D2 Eddy Viscosity=0.3
UNET D2 Transverse Eddy Viscosity=0.1
UNET D2 Smagorinsky Mixing=0
UNET D2 BCVolumeCheck=0
UNET D2 Cores=0
UNET D2 SolverType=PARDISO (Direct)
UNET D2 Minimum Iterations= 2147483647
UNET D2 Maximum Iterations= 2147483647
UNET D2 Restart Number= 10
UNET D2 Relaxation Coeff=1.3
UNET D2 SOR Precondition Iterations= 10
UNET D2 ILUT Maximum Fill= 8
UNET D2 ILUT Tolerance=1E-08
UNET D1D2 MaxIter= 0
UNET D1D2 ZTol=0.01
UNET D1D2 QTol=0.1
UNET D1D2 MinQTol=1
Write IC File= 0
Write IC File at Fixed DateTime=0
Write IC File at Sim End=0
Echo Input=False
Echo Parameters=False
Echo Output=False
Write Detailed= 0
HDF Write Warmup=0
HDF Write Time Slices=0
HDF Flush=0
HDF Compression= 1
HDF Chunk Size= 1
HDF Spatial Parts= 1
HDF Use Max Rows=0
HDF Fixed Rows= 1
Calibration Method= 0
Calibration Iterations= 20
Calibration Max Change=0.05
Calibration Tolerance=0.2
Calibration Maximum=1.5
Calibration Minimum=0.5
Calibration Optimization Method= 1
WQ AD Non Conservative
WQ ULTIMATE=-1
WQ Max Comp Step=1HOUR
WQ Output Interval=15MIN
WQ Output Selected Increments= 0
WQ Output face flow=0
WQ Output face velocity=0
WQ Output face area=0
WQ Output face dispersion=0
WQ Output cell volume=0
WQ Output cell surface area=0
WQ Output cell continuity=0
WQ Output cumulative cell continuity=0
WQ Output face conc=0
WQ Output face dconc_dx=0
WQ Output face courant=0
WQ Output face peclet=0
WQ Output face adv mass=0
WQ Output face disp mass=0
WQ Output cell mass=0
WQ Output cell source sink temp=0
WQ Output nsm pathways=0
WQ Output nsm derived pathways=0
WQ Create Restart=0
WQ Fixed Restart=0
WQ System Summary=0
WQ Write To DSS=0
Sorting and Armoring Iterations= 10
XS Update Threshold= 0.02
Bed Roughness Predictor= 0
Hydraulics Update Threshold= 0.02
Energy Slope Method= 1
Volume Change Method= 1
Sediment Retention Method= 0
Sediment TS Multiplier= 1
Warm Up Method= 0
XS Weighting Method= 0
Number of US Weighted Cross Sections= 1
Number of DS Weighted Cross Sections= 1
Upstream XS Weight=0
Main XS Weight=1
Downstream XS Weight=0
Number of DS XS's Weighted with US Boundary= 1
Upstream Boundary Weight= 1
Weight of XSs Associated with US Boundary= 0
Number of US XS's Weighted with DS Boundary= 1
Downstream Boundary Weight= 0.5
Weight of XSs Associated with DS Boundary= 0.5
Percentile Method= 0
Sediment Output Level= 3
Mass or Volume Output= 0
Output Increment Type= 1
Profile and TS Output Increment= 1
Transport Output Increment 1
XS Output Flag= 0
XS Output Increment= 10
Read HDF5 Sediment Hotstart= 0
Sediment Hotstart Type= 0
Write Gradation File= 0
Read Gradation Hotstart= 0
Write HDF5 File= 1
Write Binary Output= 1
Write DSS Sediment File= 0
DSS Sediment Output Type= 1
SV Curve= 0
Specific Gage Flag= 0
Subcell Erosion Methods= 0
Subcell Deposition Methods= 0
Advection Scheme= 1
Matrix Solver= 0
Implicit Weighting Factor= 1
Maximum Outer Loop Convergence Iterations= 5
Convergence Maximum Absolute= 0.001
Convergence RMSE= 0.0001
Grain Fractions Max Abs Error= 0.001
Max Subgrid Regions= 1
Max Subgrid Length Scale= 3.402823E+38
Initial Layer Thickness= 3.402823E+38
Min Layer Thickness= 3.402823E+38
Max Layer Thickness= 3.402823E+38
Number of Layers= 5

--- ISLNDLCKRN.f01 (steady flow) ---

Flow Title=Flow
Program Version=6.00
Number of Profiles= 6
Profile Names=01pct,10pct,04pct,02pct,0_2pct,01plus
River Rch & RM=ISLNDLCKRN,Main,21424
     566     299     398     479     791     837
River Rch & RM=ISLNDLCKRN,Main,18934
     630     334     444     534     878     932
River Rch & RM=ISLNDLCKRN,Main,15363
     700     373     494     594     974    1040
River Rch & RM=ISLNDLCKRN,Main,13887
     780     417     552     663    1080    1150
River Rch & RM=ISLNDLCKRN,Main,8935
     983     530     698     836    1360    1450
River Rch & RM=ISLNDLCKRN,Main,5824
    1100     595     781     934    1510    1620
Boundary for River Rch & Prof#=ISLNDLCKRN,Main            , 1
Up Type= 0
Dn Type= 3
Dn Slope=0.01489
Boundary for River Rch & Prof#=ISLNDLCKRN,Main            , 2
Up Type= 0
Dn Type= 3
Dn Slope=0.01489
Boundary for River Rch & Prof#=ISLNDLCKRN,Main            , 3
Up Type= 0
Dn Type= 3
Dn Slope=0.01489
Boundary for River Rch & Prof#=ISLNDLCKRN,Main            , 4
Up Type= 0
Dn Type= 3
Dn Slope=0.01489
Boundary for River Rch & Prof#=ISLNDLCKRN,Main            , 5
Up Type= 0
Dn Type= 3
Dn Slope=0.01489
Boundary for River Rch & Prof#=ISLNDLCKRN,Main            , 6
Up Type= 0
Dn Type= 3
Dn Slope=0.01489
DSS Import GetInterval= 0
DSS Import GetPeak= 0
DSS Import FillOption= 0

--- ISLNDLCKRN.g01 (geometry) ---

Geom Title=Geometry
Program Version=6.00

River Reach=ISLNDLCKRN      ,Main
Reach XY= 30
     2221292.287      408082.629     2221362.623       407947.97
     2221110.652      407868.299     2220046.943      408356.533
2218505.49678431408592.2392484742216915.62284338409552.823664982
2216141.17834047409565.204530795     2215468.124      409983.775
     2215029.952      409905.631     2214638.487      409375.766
2214198.66318709409280.444617101     2213081.659      409751.279
     2212808.656      410114.855     2212168.497      410210.347
     2211460.621      409925.0072211411.64687652409090.755786536
     2210808.336      408741.0842210557.87944713408316.140513064
2210856.81331754407802.804200881 2210434.7748961407280.754727268
     2210666.279      406768.5792210557.11097959 406330.03617349
     2209587.671      406156.468     2208773.638      406563.992
     2208271.565      406543.187     2208070.344      406992.561
     2207465.318      407239.239     2207123.027      407640.268
     2206408.032      407717.876     2205733.194      408091.116

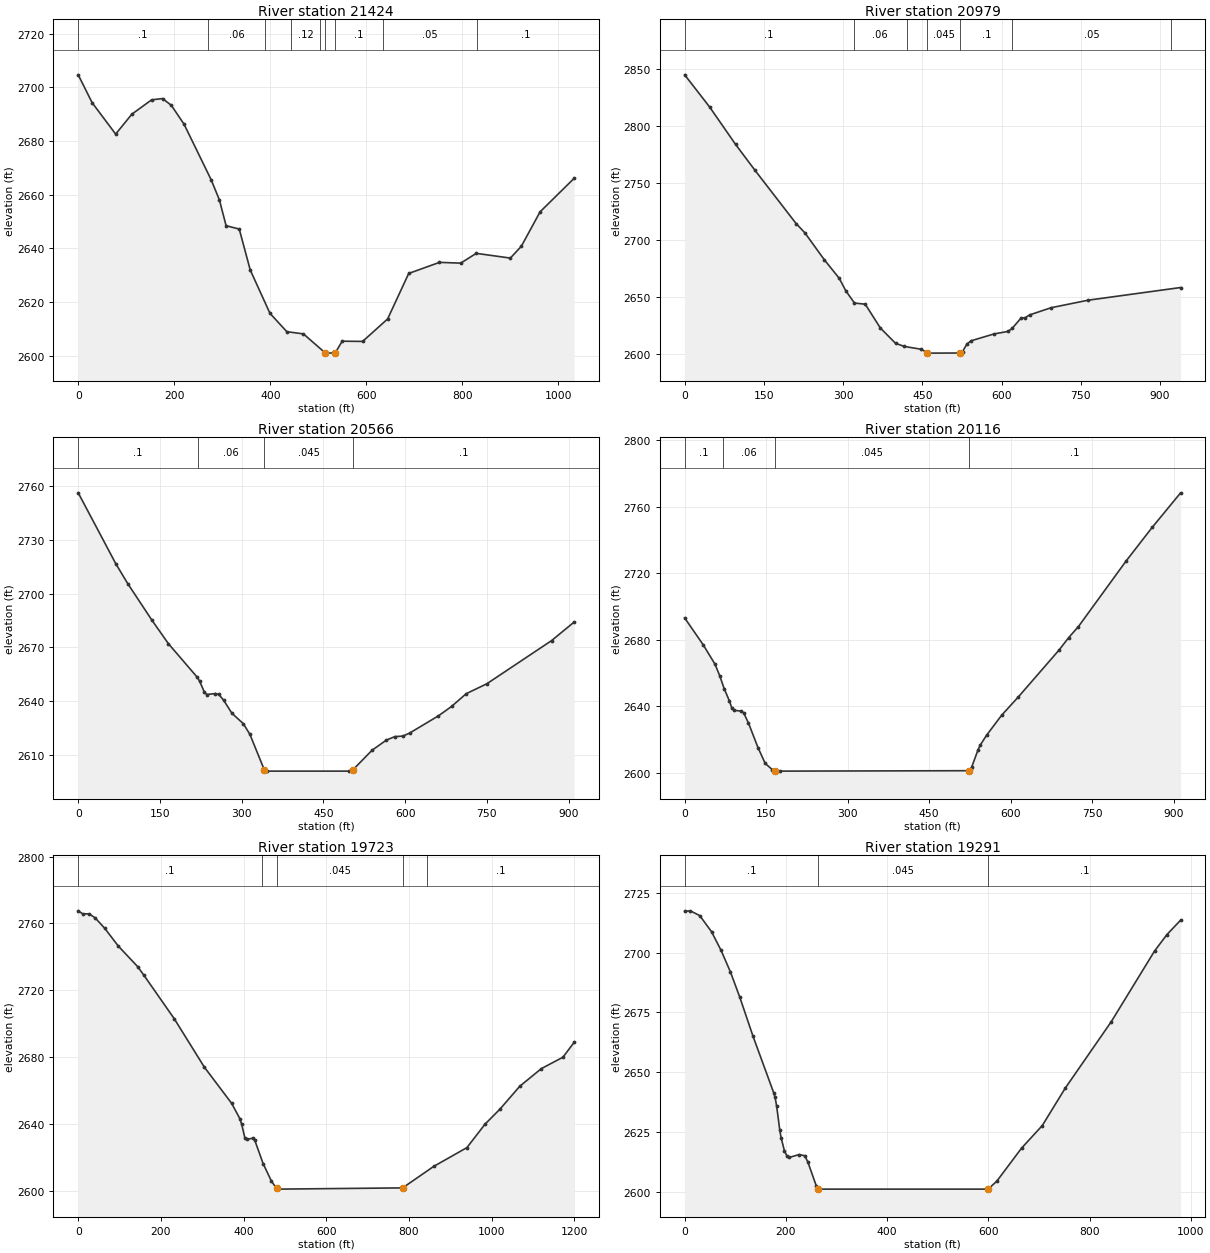
Type RM Length L Ch R = 1 ,21424   ,444.8,444.8,444.8
XS GIS Cut Line= 4
2221521.79927518407455.3493781052221312.42465588407835.529607889
2221159.25059228408076.8614059262221121.78355514408387.617419836
#Sta/Elev= 30
       0 2704.68      29  2694.3      78  2682.6   111.7 2690.02   152.8 2695.35
   175.6 2695.84   193.9 2693.32   220.5 2686.27     277 2665.54   294.1 2658.05
     308 2648.48   335.4 2647.22   358.3 2631.96   399.4 2615.82   434.5 2608.99
   469.1 2608.16   513.6 2601.22   516.5    2601   535.5 2601.11   549.7 2605.45
   592.3 2605.36   644.4 2613.73   688.3 2630.68   752.4 2634.81   796.7 2634.53
     829 2638.17     900 2636.41   922.9 2640.81   961.9 2653.63  1032.9 2666.13
#Mann= 9 ,-1,0
       0      .1       0     270     .06       0     390      .1       0
  444.02     .12       0  504.02      .1       0   513.6    .045       0
   535.5      .1       0  634.02     .05       0  829.86      .1       0
Bank Sta=513.6,535.5
XS Rating Curve= 0 ,0
Exp/Cntr(USF)=0,0
Exp/Cntr=0.3,0.1

Type RM Length L Ch R = 1 ,20979   ,431,413.7,402.8
XS GIS Cut Line= 2
2220746.33711739407483.020419219     2220944.228      408400.735
#Sta/Elev= 30
       0 2845.03    47.2 2816.84    96.3 2784.06   133.2 2761.24   210.9 2714.64
   227.3 2706.63   264.1 2683.02   292.6 2666.59     305 2655.66   321.4  2644.9
   341.8 2643.91   370.5 2622.98   399.1 2609.64   415.5  2606.9   448.2 2604.36
   459.5 2601.13   460.5    2601   522.1 2601.11     526 2602.38   534.2  2608.9
   542.3 2611.85   585.7 2617.84   611.9 2620.01   620.1 2622.77   636.5 2631.66
   644.6 2632.04   652.8 2634.49   693.7 2640.82   763.3 2647.38   938.8 2658.53
#Mann= 7 ,-1,0
       0      .1       0     320     .06       0     420      .1       0
   459.5    .045       0   522.1      .1       0     620     .05       0
     920      .1       0
Bank Sta=459.5,522.1
XS Rating Curve= 0 ,0
Exp/Cntr=0.3,0.1

Type RM Length L Ch R = 1 ,20566   ,462.7,449.2,449.4
XS GIS Cut Line= 2
2220281.48637504407694.4283115112220658.16437504408522.808311511
#Sta/Elev= 30
       0 2756.23    68.9 2716.72    90.9 2705.58   134.8 2685.39   165.6 2672.05
   218.6  2653.3   222.7  2651.2   231.5 2645.07   235.9 2643.73   251.8 2644.28
   257.9 2643.78   266.7 2640.62     282 2633.29   303.1 2627.41     315 2621.52
   341.4 2601.76   345.8    2601   496.5    2601     504 2601.71   539.1 2612.63
   565.5 2618.32     581 2620.25     596 2620.55   608.2 2622.24   660.9 2631.83
   685.1 2637.09   711.9 2644.19   749.6 2649.69   868.7 2673.83     910 2684.16
#Mann= 4 ,-1,0
       0      .1       0     220     .06       0   341.4    .045       0
     504      .1       0
Bank Sta=341.4,504
XS Rating Curve= 0 ,0
Exp/Cntr=0.3,0.1

Type RM Length L Ch R = 1 ,20116   ,287.8,393.2,418.1
XS GIS Cut Line= 2
2219898.59774041407922.3551038372220277.99874041408752.809103837
#Sta/Elev= 30
       0 2693.17    33.9 2677.09    55.9 2665.29    64.7 2658.19    72.7 2650.64
    82.3 2643.24    86.7 2639.05    91.1 2637.54   104.3 2637.15   108.6 2636.05
   117.4 2629.96     135 2615.14   148.2 2605.66   161.4 2601.86   166.3 2601.31
   174.6    2601   523.6 2601.26   526.4 2601.99   528.6 2603.59   539.6 2613.42
     544 2616.61   555.7 2622.55   583.6 2634.66   614.4 2645.69   689.1  2673.8
   706.7 2681.23   724.8 2687.93   812.3 2727.26   860.6 2747.61     913 2768.42
#Mann= 4 ,-1,0
       0      .1       0      70     .06       0   166.3    .045       0
   523.6      .1       0
Bank Sta=166.3,523.6
XS Rating Curve= 0 ,0
Exp/Cntr=0.3,0.1

Type RM Length L Ch R = 1 ,19723   ,479.8,432.6,423.8
XS GIS Cut Line= 4
2219827.91466439407686.1731474482219670.15710832407947.280487559
2219701.19784037408386.0565788452219726.55184037408840.356578846
#Sta/Elev= 30
       0 2767.57    10.7 2765.79    26.9 2765.73    40.9 2763.37    64.3 2757.08
      97 2746.48   143.7 2734.21   159.3 2728.88   232.5 2702.94   305.1 2674.04
   371.1 2652.39   391.2 2643.13   395.6 2639.73   403.2 2631.69   407.2 2630.74
   423.3 2631.54   427.3  2630.2   447.3 2616.33   467.4 2605.82479.79182601.431
   483.4    2601 784.8382601.739   860.2 2614.61   940.4 2625.84   984.4 2639.92
  1020.5  2648.9  1068.6 2662.64  1120.6 2673.14  1172.7 2679.94  1199.9 2688.87
#Mann= 5 ,-1,0
       0      .1       0  445.06     .06       0479.7918    .045       0
 784.838    .025       0  844.94      .1       0
Bank Sta=479.7918,784.838
XS Rating Curve= 0 ,0
Exp/Cntr=0.3,0.1

Type RM Length L Ch R = 1 ,19291   ,315.6,152.6,152
XS GIS Cut Line= 4
2219089.00816562408003.5025036592219212.40203707408212.070905855
2219317.23222875 408610.64403047 2219390.3949667408927.318567835
#Sta/Elev= 30
       0 2717.23    11.2 2717.44    29.8 2715.43    53.1 2708.68    71.7 2700.97
    90.3 2691.91   108.8 2681.33   134.9 2665.01   175.8 2641.33   178.6 2639.38
   181.7 2635.65   187.9 2625.57   190.4 2622.56   197.1 2616.96   202.1 2614.84
   206.4 2614.25   226.2 2615.47   237.1 2614.97   243.1 2612.46     260 2602.31
   264.2    2601   599.2    2601   616.4  2604.3   665.3 2618.14   706.3  2627.6
   751.5 2643.21   842.5 2671.05     928 2700.61   952.5 2707.51   979.5 2713.54
#Mann= 3 ,-1,0
       0      .1       0   264.2    .045       0   599.2      .1       0
Bank Sta=264.2,599.2
XS Rating Curve= 0 ,0
Exp/Cntr(USF)=0,0
Exp/Cntr=0.3,0.1

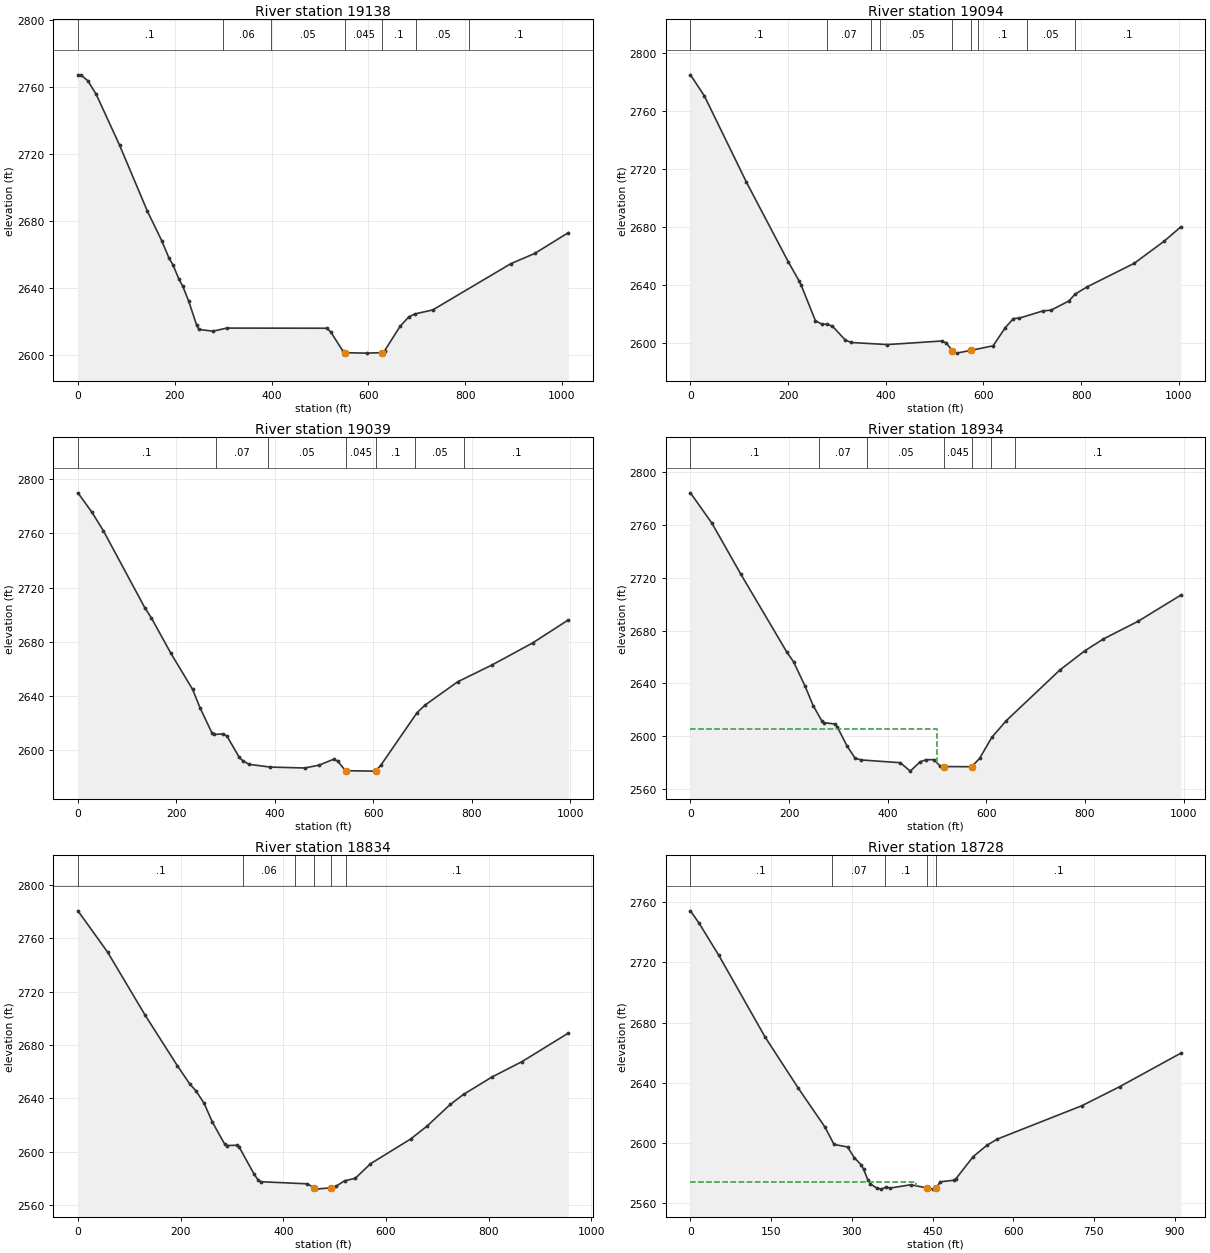
Type RM Length L Ch R = 1 ,19138   ,56.6,43.8,69.8
XS GIS Cut Line= 3
2218981.84963004 408006.835671342219035.54433446408123.894419906
2219256.04871657408980.668492012
#Sta/Elev= 30
       0 2767.17       7 2766.82    20.2 2763.71    37.8 2755.49    86.2 2725.02
   143.5 2685.68   173.1 2668.09   187.9 2657.82   196.1 2653.72   208.6 2645.13
   216.8 2640.69   228.9 2631.89   245.3 2617.59   249.9 2614.99   278.8 2613.97
   307.7 2615.81   514.2 2615.72   522.5 2613.49   546.8 2602.36   551.4  2601.1
   596.7 2600.84   628.8 2601.13     634 2602.36   665.8 2616.93   683.6 2622.47
     696 2624.26   733.1 2626.64   894.2 2654.24   943.8 2660.39  1013.5 2672.85
#Mann= 7 ,-1,0
       0      .1       0  298.79     .06       0  398.79     .05       0
   551.4    .045       0   628.8      .1       0  698.79     .05       0
  808.79      .1       0
Bank Sta=551.4,628.8
XS Rating Curve= 0 ,0
Exp/Cntr=0.3,0.1

Type RM Length L Ch R = 1 ,19094   ,40.7,55.5,68.9
XS GIS Cut Line= 4
2218918.19647294408022.6278258632219021.36394908408282.063684979
2219127.56576275408646.1841890012219183.70100712408987.547161522
#Sta/Elev= 30
       0 2784.77    28.6 2770.23   114.7 2710.88   200.6 2655.94   222.2 2643.13
   226.6 2640.15     256 2615.52   269.6 2613.13   279.2 2613.14   290.8  2611.8
   316.2  2602.6   328.3 2600.58   403.3 2599.13   515.8 2601.61   524.1 2600.09
   536.6  2594.9   544.9 2593.24   574.1 2595.11   619.9  2598.3   644.9 2610.84
   661.5 2617.03   673.7 2617.35   722.3 2622.33   738.5 2622.82     775 2629.12
   787.5 2633.76   811.5 2638.71   908.8 2655.05   969.6 2670.14  1004.4 2680.17
#Mann= 9 ,-1,0
       0      .1       0   279.2     .07       0   369.2     .06       0
   389.2     .05       0   536.6    .045       0   574.1     .05       0
   589.2      .1       0  688.49     .05       0  788.49      .1       0
Bank Sta=536.6,574.1
XS Rating Curve= 0 ,0
Exp/Cntr(USF)=0,0
Exp/Cntr=0.3,0.1

Type RM Length L Ch R = 1 ,19039   ,102.6,104.5,105.5
XS GIS Cut Line= 5
 2218865.0955661408030.2136696972218986.46906744408289.649528813
2219053.22449318 408515.707675062219047.15581811408638.598345167
2219129.08293152408979.961317688
#Sta/Elev= 30
       0    2790    28.6 2775.58    51.9 2761.84   135.8 2705.13     149  2697.7
   188.7 2671.52   232.9 2644.79   248.2 2631.03   272.3 2612.59   277.1 2611.55
   294.3 2611.86   302.6 2610.37   327.6 2594.62   335.7 2591.81   348.3  2589.4
   390.2 2587.41   461.3 2586.73   490.4 2588.92   519.5 2593.22   527.6 2591.77
   543.6 2584.72   603.7 2584.41   604.7 2584.57   615.3 2588.79     689 2627.69
   705.4 2633.29   771.2 2650.38   841.2 2662.85   923.8 2679.16   996.2 2696.15
#Mann= 7 ,-1,0
       0      .1       0     280     .07       0  386.42     .05       0
   543.6    .045       0   604.7      .1       0  685.17     .05       0
  785.17      .1       0
Bank Sta=543.6,604.7
XS Rating Curve= 0 ,0
Exp/Cntr(USF)=0,0
Exp/Cntr=0.3,0.1

Type RM Length L Ch R = 1 ,18934   ,102.5,99.9,97.2
XS GIS Cut Line= 5
2218825.41281294408052.5081536092218953.66043564408321.951457684
2218952.43152894408508.7452762462218942.22398918408611.722319079
2219062.37272539408999.255822215
#Sta/Elev= 30
       0 2784.54    43.7 2761.41   101.6 2723.21   195.7 2663.56     209 2656.43
   232.3    2638   248.8 2623.18   266.5 2611.47     271 2610.14   293.1 2609.22
   297.6 2607.02   317.6 2592.46   333.6 2583.41   345.6 2581.94   425.6 2579.82
   445.6 2573.44   465.6 2580.45   477.6  2582.1   493.7 2582.12   505.7  2577.5
 514.8552576.902   570.2 2576.78   586.1 2583.04   611.2 2599.13   640.5 2611.77
   749.3 2650.24   799.6 2664.72   837.3 2673.69   907.9 2687.17   994.4 2706.98
#Mann= 7 ,-1,0
       0      .1       0     260     .07       0  358.41     .05       0
 514.855    .045       0   570.2      .1       0  608.69     .05       0
  658.69      .1       0
#XS Ineff= 2 , 0
          499.72 2605.68
Permanent Ineff=
       F       F
Bank Sta=514.855,570.2
XS Rating Curve= 0 ,0
Exp/Cntr(USF)=0,0
Exp/Cntr=0.3,0.1

Type RM Length L Ch R = 1 ,18834   ,110,106.1,102.7
XS GIS Cut Line= 5
2218805.81903029408063.3312013842218809.91341524408375.528053934
 2218846.7628798408500.4067949542218851.88086099408579.223705269
2218990.06635311408990.709392893
#Sta/Elev= 30
       0 2780.58    57.9 2749.57   130.5 2702.63   193.7  2664.5   217.9  2650.8
   229.9 2645.69   245.9 2636.25   261.9 2622.27   285.9 2605.71   289.9 2604.69
   309.9 2604.87   313.9  2603.7   343.1 2583.31   350.8 2578.96   355.7 2577.56
   447.2 2575.97   459.5  2573.1   463.3    2572   493.2 2573.01   503.3 2574.27
   519.4 2578.26   540.3 2580.08   569.9 2591.02     648 2609.52   679.6 2619.07
   725.3 2635.44   751.3 2643.03   806.2 2655.94   865.3  2667.6   955.5 2688.97
#Mann= 6 ,-1,0
       0      .1       0  322.22     .06       0  422.22      .1       0
   459.5    .045       0   493.2     .05       0  521.41      .1       0
Bank Sta=459.5,493.2
XS Rating Curve= 0 ,0
Exp/Cntr(USF)=0,0
Exp/Cntr=0.3,0.1

Type RM Length L Ch R = 1 ,18728   ,150.8,148.9,147.4
XS GIS Cut Line= 4
2218631.78232415408129.4005398062218668.65713442408318.206664613
2218757.71000711408597.648437551     2218832.405      409017.102
#Sta/Elev= 30
       0  2754.3    16.1 2746.05    52.8 2724.72   138.3 2670.78   200.7 2636.42
   250.1 2610.69   266.9 2599.16   292.1 2597.48   304.6 2590.37   317.2 2585.73
   321.7 2582.85   329.8 2575.66     334 2573.19   346.6 2570.07     355  2569.5
   363.4 2570.82   371.8 2570.25   409.6 2572.38     439 2570.36   451.6 2569.49
457.16852570.273   464.2 2574.32   489.2  2575.4   493.3 2576.31   525.8 2591.14
   551.2 2598.64   570.5 2602.73   727.9 2624.92   797.8 2637.51   911.7  2659.8
#Mann= 5 ,-1,0
       0      .1       0  262.37     .07       0  362.37      .1       0
     439    .045       0457.1685      .1       0
#XS Ineff= 2 , 0
          418.92 2574.27
Permanent Ineff=
       F       F
Bank Sta=439,457.1685
XS Rating Curve= 0 ,0
Exp/Cntr=0.3,0.1

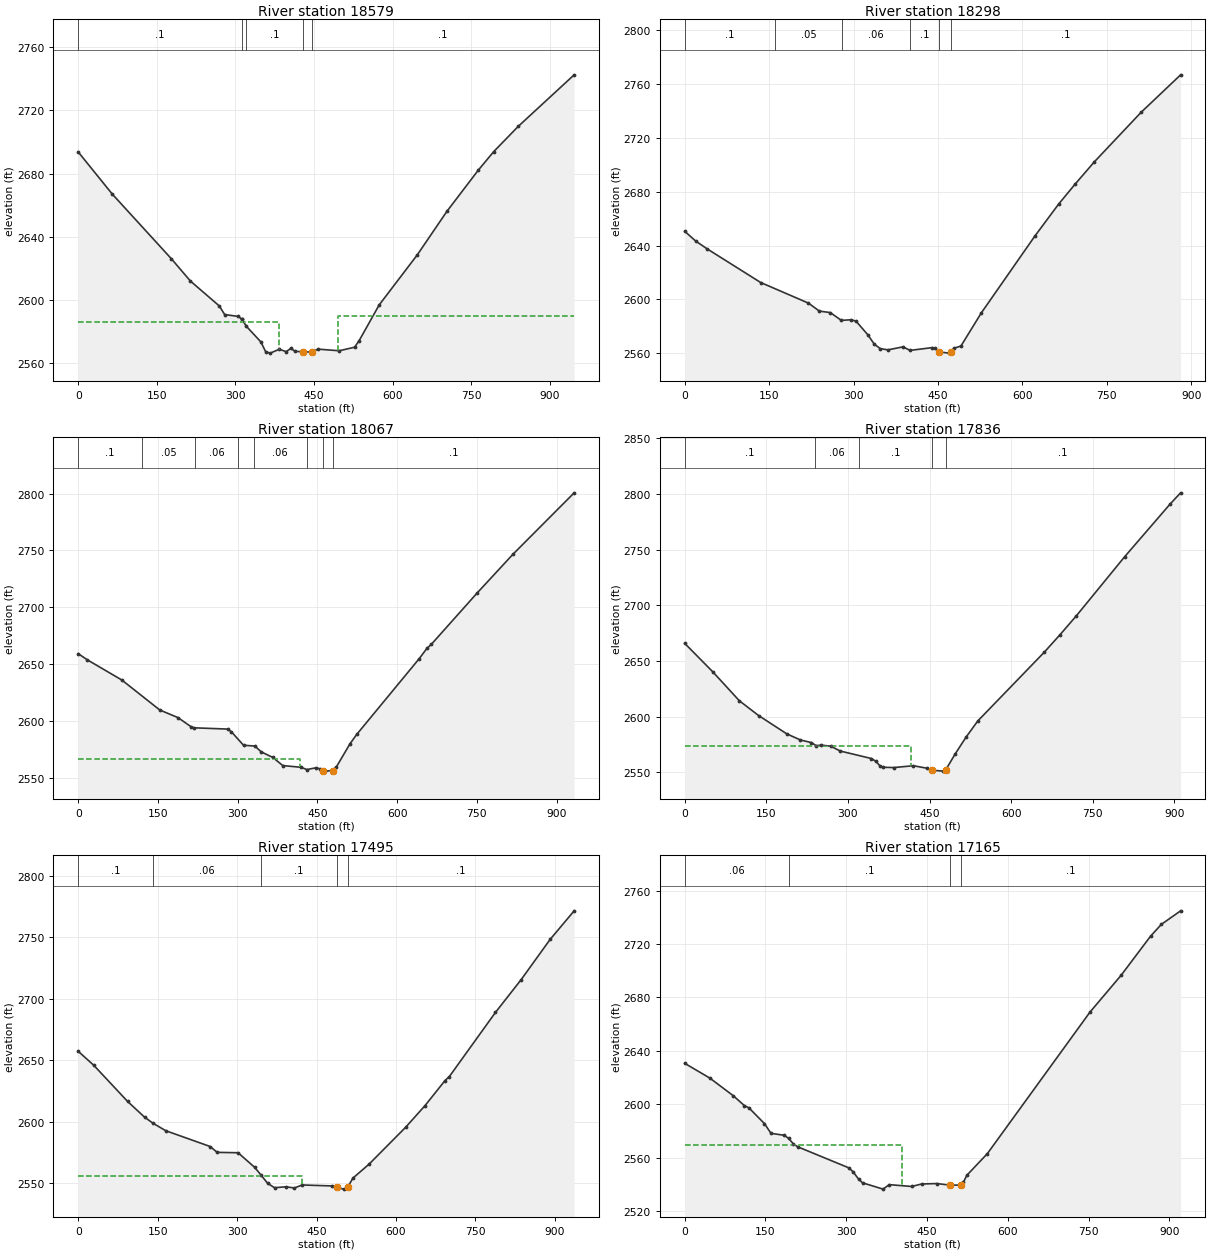
Type RM Length L Ch R = 1 ,18579   ,277.3,280.9,279.1
XS GIS Cut Line= 3
2218432.13302949408188.1647333482218679.39508729 408769.54872445
2218686.45387061409083.658817537
#Sta/Elev= 30
       0 2693.75    64.8 2667.15   177.7 2626.17   214.1 2612.04   269.2  2596.3
   279.3 2590.89   305.4 2589.67   311.9    2588   311.9 2587.97     321 2583.36
   348.5 2573.53   357.6  2567.3   366.2 2566.47   383.6 2568.92   396.7  2567.4
   405.3 2569.41     414 2567.64   429.4 2567.23  445.24  2567.2   457.5 2568.99
   497.9 2567.97   527.1  2570.2   535.8 2574.32   574.1 2596.97     647 2628.73
   703.4 2656.23   763.4 2682.33   792.6 2693.96   839.3 2709.91     946 2742.54
#Mann= 5 ,-1,0
       0      .1       0   311.9     .06       0     321      .1       0
   429.4    .045       0  445.24      .1       0
#XS Ineff= 2 , 0
          382.49  2586.1  496.16         2589.78
Permanent Ineff=
       F       F
Bank Sta=429.4,445.24
XS Rating Curve= 0 ,0
Exp/Cntr(USF)=0,0
Exp/Cntr=0.3,0.1

Type RM Length L Ch R = 1 ,18298   ,231.5,231.1,230.9
XS GIS Cut Line= 3
  2218176.307344  408353.00893672218430.15921099408716.385601144
2218573.46268429409129.918481243
#Sta/Elev= 30
       0 2650.59    19.7 2643.27    39.2  2637.7     135 2612.54   219.8 2597.25
   239.3 2591.31   258.6 2590.23   278.3 2584.44   295.9 2584.91   304.5 2583.78
     325  2573.9   336.9 2566.73   347.6 2563.42   361.3 2562.57   387.8 2564.79
   400.3 2562.16   439.5 2564.21   445.5 2563.63   451.8 2561.05   469.5 2560.13
   472.62560.952     478 2563.73   490.7  2565.4   527.2 2590.18   621.9 2646.94
   664.2 2670.73   693.7 2685.66   727.7 2702.11   810.5 2738.77   880.9 2766.68
#Mann= 6 ,-1,0
       0      .1       0     160     .05       0     280     .06       0
     400      .1       0   451.8    .045       0   472.6      .1       0
Bank Sta=451.8,472.6
XS Rating Curve= 0 ,0
Exp/Cntr(USF)=0,0
Exp/Cntr=0.3,0.1

Type RM Length L Ch R = 1 ,18067   ,230.5,230.8,231.2
XS GIS Cut Line= 2
2218059.00206105408372.956506719 2218378.4443803409249.525556702
#Sta/Elev= 30
       0 2659.11    17.3 2653.63    82.2 2635.85   153.5 2609.47   187.6 2602.81
   213.1 2594.51   217.4 2593.81   281.2 2592.69   288.2 2590.32     311 2578.44
   332.3 2577.76   344.3 2572.63   366.2 2567.68   384.9 2560.55   419.2 2559.04
   430.2 2557.03   447.4 2558.62   455.8  2557.6   459.8  2556.2   464.3 2555.66
   478.5 2556.14   485.6  2559.3   511.1 2579.59   523.9 2587.96   641.5 2654.69
   655.9  2663.7   664.4 2667.34   749.9 2712.22   817.6  2746.5     933 2800.73
#Mann= 8 ,-1,0
       0      .1       0     120     .05       0     220     .06       0
     300     .07       0     330     .06       0     430      .1       0
   459.8    .045       0   478.5      .1       0
#XS Ineff= 2 , 0
          417.76 2566.29
Permanent Ineff=
       F       F
Bank Sta=459.8,478.5
XS Rating Curve= 0 ,0
Exp/Cntr=0.3,0.1

Type RM Length L Ch R = 1 ,17836   ,341.7,341.9,340.8
XS GIS Cut Line= 4
2217828.86929841408458.0552619232217974.51750001408770.592027875
2217986.65485015408844.9332974472218142.92323312409310.704108841
#Sta/Elev= 30
       0 2665.96      52 2640.18   100.5 2614.33   135.8 2601.11   187.7 2584.61
   212.5 2579.19   232.9 2576.78   241.7    2574   250.6 2574.51   268.2 2573.59
   285.9  2569.2   343.2 2562.48   351.5 2559.89   359.6  2555.5   363.6 2554.64
   383.9 2554.35   420.4 2556.01   445.7 2553.72   454.1 2551.98   475.2 2551.16
   479.5  2552.1   497.3 2566.75   517.4  2581.9   538.7 2596.24   660.9 2658.01
   690.1 2673.86     720 2690.78   808.6 2743.76   892.2 2791.11   911.4 2801.12
#Mann= 5 ,-1,0
       0      .1       0     240     .06       0     320      .1       0
   454.1    .045       0   479.5      .1       0
#XS Ineff= 2 , 0
          416.34 2573.91
Permanent Ineff=
       F       F
Bank Sta=454.1,479.5
XS Rating Curve= 0 ,0
Exp/Cntr(USF)=0,0
Exp/Cntr=0.3,0.1

Type RM Length L Ch R = 1 ,17495   ,331.4,329.1,327.6
XS GIS Cut Line= 4
2217644.34711311408539.9511440362217648.13168526408892.444154057
2217788.36436985409221.0185464132217917.09576141409407.467857507
#Sta/Elev= 30
       0 2657.27    29.2 2645.95    93.2 2616.46   125.2 2603.68   141.2 2598.69
   165.2 2592.62   249.2 2579.73   262.3 2574.99   301.8 2574.68     333 2562.85
   345.1 2556.53   357.7 2549.75   370.7 2546.22   392.5 2546.97     408 2545.99
   422.9 2548.44   479.4 2547.66   488.1 2546.53   501.2 2545.06   508.6 2546.53
   518.6 2554.02     549 2565.34   618.3 2595.47   654.9 2613.12   692.5 2633.44
   700.6 2636.64   787.7 2688.88   836.3 2715.62   890.9  2748.3   936.3 2771.59
#Mann= 5 ,-1,0
       0      .1       0   141.2     .06       0   345.1      .1       0
   488.1    .045       0   508.6      .1       0
#XS Ineff= 2 , 0
           422.9 2555.99
Permanent Ineff=
       F       F
Bank Sta=488.1,508.6
XS Rating Curve= 0 ,0
Exp/Cntr=0.3,0.1

Type RM Length L Ch R = 1 ,17165   ,269.9,270.6,270.8
XS GIS Cut Line= 4
2217287.12295425408785.300146748 2217362.5483349409099.210594107
2217559.07881257 409371.487193382217775.59263912409519.454711825
#Sta/Elev= 30
       0 2630.62    47.1 2619.43    90.5 2606.23   110.9 2598.89   119.2 2597.28
     148 2585.48   160.3 2578.15     185 2576.67   193.2 2574.28   201.5 2570.39
   209.7 2568.09   304.3 2552.37   312.6 2549.42   322.8 2543.91   330.2 2541.08
   368.4 2536.34   379.9  2539.7   421.3 2538.33     440 2540.19   468.7 2540.51
493.52232539.278 513.0852539.416   517.4 2541.35   523.8 2546.65   562.1 2562.97
   752.7 2669.03   810.2 2696.44     865  2725.8   885.1 2734.69   920.9 2744.85
#Mann= 4 ,-1,0
       0     .06       0   193.2      .1       0493.5223    .045       0
 513.085      .1       0
#XS Ineff= 2 , 0
          403.99 2569.06
Permanent Ineff=
       F       F
Bank Sta=493.5223,513.085
XS Rating Curve= 0 ,0
Exp/Cntr=0.3,0.1

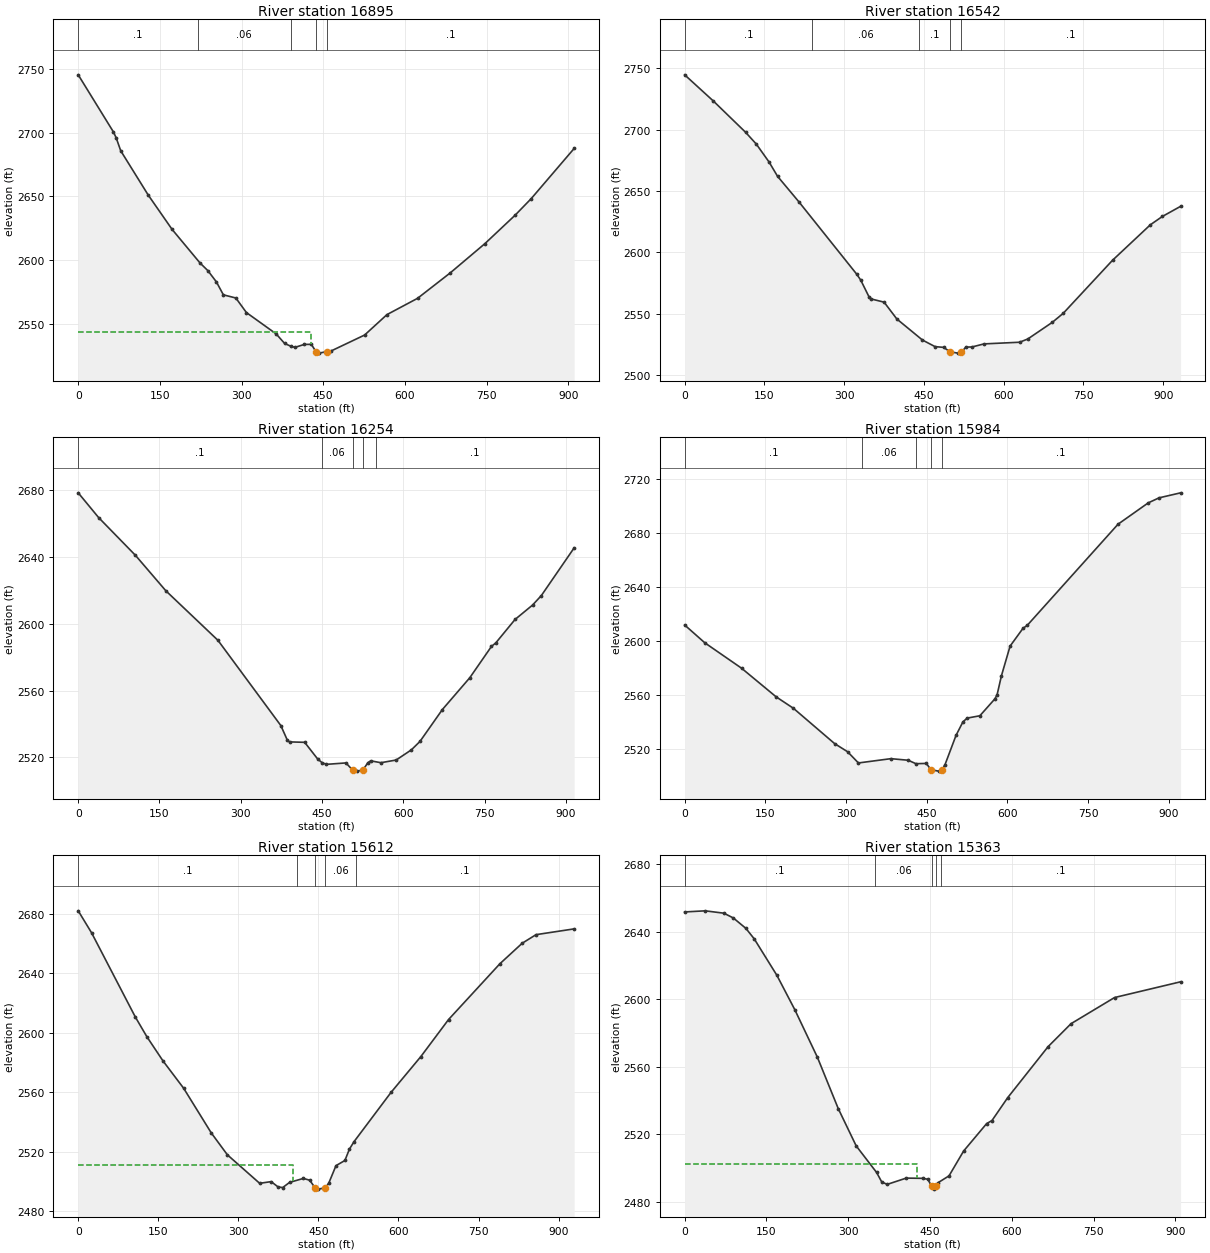
Type RM Length L Ch R = 1 ,16895   ,355,353.3,349.7
XS GIS Cut Line= 4
 2216945.3526595408950.5721462192217197.30144621409284.664310309
2217229.20038976409344.653368327 2217483.7216595409684.233146219
#Sta/Elev= 30
       0 2745.26    64.5 2700.57    69.6 2695.99    78.1 2685.66   128.5 2650.99
   172.4    2624   223.9 2597.57   238.1 2591.66   253.8 2582.81   266.6 2572.66
   289.5 2570.19   308.9 2558.76   363.4 2542.07     379 2534.57     390 2532.42
     398 2531.45   415.2 2533.77   428.1 2533.84   437.1 2527.81   441.6 2526.94
   456.4 2528.05   464.3 2528.61     526 2541.14     567 2557.15   623.2 2569.93
   683.2 2589.87     747 2612.88     802 2634.98     832 2648.17   910.8  2687.5
#Mann= 5 ,-1,0
       0      .1       0     220     .06       0     390      .1       0
   437.1    .045       0   456.4      .1       0
#XS Ineff= 2 , 0
          427.61 2543.56
Permanent Ineff=
       F       F
Bank Sta=437.1,456.4
XS Rating Curve= 0 ,0
Exp/Cntr=0.3,0.1

Type RM Length L Ch R = 1 ,16542   ,277.2,287.3,293.8
XS GIS Cut Line= 4
2216888.66203627409026.7598142682216916.76296503409501.311287033
 2216989.8814357409590.8132096712217203.71120169409857.485963804
#Sta/Elev= 30
       0  2744.8    54.2 2723.34   114.6 2697.95   134.7 2688.35   158.7 2673.74
   174.7 2662.06   214.8 2641.28   323.4 2582.37   331.1 2577.48     347 2563.55
     351 2562.06   375.1 2559.47   399.1 2545.73   447.2  2528.6   470.9 2523.23
   487.1 2522.61   499.7 2518.83   514.7 2517.92   520.4 2518.75   528.9 2522.86
   540.3 2522.93     563 2525.44   629.9  2526.8   645.3 2529.44   691.4    2543
   711.9 2550.33   804.8 2593.65     876 2622.59   898.7  2629.4   932.8  2637.6
#Mann= 5 ,-1,0
       0      .1       0     240     .06       0     440      .1       0
   499.7    .045       0   520.4      .1       0
Bank Sta=499.7,520.4
XS Rating Curve= 0 ,0
Exp/Cntr(USF)=0,0
Exp/Cntr=0.3,0.1

Type RM Length L Ch R = 1 ,16254   ,261.8,269.9,278.6
XS GIS Cut Line= 4
2216651.31024936 409111.542552332216670.97275658409590.816165749
2216682.03291689409674.3818214222216684.49073029 410025.84913793
#Sta/Elev= 30
       0 2678.14    37.7 2663.35   105.7 2640.77   161.8 2619.59   257.9 2590.02
     374 2539.08     386 2530.35     390 2529.32     418 2529.06     442 2519.09
     450 2516.93     458  2515.9   494.2 2516.75   506.3 2512.55   514.3 2511.85
   525.6 2512.49   534.5 2516.84   539.9    2518   558.7 2516.88   586.8 2518.48
   614.8 2524.53   630.8 2529.58   672.2 2548.66   722.8 2567.66   762.8 2586.38
   770.8 2588.48   806.3 2602.47   838.6 2611.07   854.8 2616.73   915.4 2645.26
#Mann= 5 ,-1,0
       0      .1       0     450     .06       0   506.3    .045       0
   525.6     .06       0  549.68      .1       0
Bank Sta=506.3,525.6
XS Rating Curve= 0 ,0
Exp/Cntr(USF)=0,0
Exp/Cntr=0.3,0.1

Type RM Length L Ch R = 1 ,15984   ,384.7,372.2,361
XS GIS Cut Line= 4
2216473.87651514409136.1334461022216425.19141636409569.924751831
2216373.18149438 409666.58002382 2216405.5849797410041.112253626
#Sta/Elev= 30
       0 2612.03    37.3  2598.9   105.7 2580.09   170.1 2558.88   202.3 2550.39
   278.8  2524.3   302.9 2518.29   323.1 2509.98   383.4 2513.16   415.6 2511.99
     430 2509.44   449.3 2509.64458.10182504.941     472 2503.94   478.1 2504.76
     484 2508.64   504.6  2530.4   517.4 2540.37   525.3 2543.16   548.9 2544.89
     577 2557.46     581 2560.53     589 2574.46   605.1 2596.42     629 2609.51
   637.2 2611.86   805.8 2686.58     862 2702.38   882.1 2706.09   922.2  2709.8
#Mann= 5 ,-1,0
       0      .1       0     330     .06       0     430      .1       0
458.1018    .045       0   478.1      .1       0
Bank Sta=458.1018,478.1
XS Rating Curve= 0 ,0
Exp/Cntr=0.3,0.1

Type RM Length L Ch R = 1 ,15612   ,252.8,249.5,247.5
XS GIS Cut Line= 2
      2215894.58      409186.042     2216242.964       410047.35
#Sta/Elev= 30
       0 2682.09      25 2667.34   106.9 2610.77   128.5 2597.51   158.7 2581.24
   197.6 2562.75   249.3 2532.75   279.5 2518.02   339.9 2498.89   361.5 2500.01
   374.5 2496.43   383.1 2496.03     396 2499.51   421.9 2502.16   433.7 2500.96
   443.5 2495.98   449.1 2494.97     463 2495.82   469.4    2499   482.9 2510.75
   499.6 2514.23   508.2 2521.94   516.8 2526.92   585.9 2559.95     642 2584.14
   693.8    2609   790.1 2646.55   831.8 2660.31   857.7 2666.07   929.1 2669.95
#Mann= 5 ,-1,0
       0      .1       0     410     .06       0   443.5    .045       0
     463     .06       0     520      .1       0
#XS Ineff= 2 , 0
          402.25 2511.14
Permanent Ineff=
       F       F
Bank Sta=443.5,463
XS Rating Curve= 0 ,0
Exp/Cntr=0.3,0.1

Type RM Length L Ch R = 1 ,15363   ,190.1,190.1,190.2
XS GIS Cut Line= 2
2215621.48643386409361.0106126482216097.07332718410136.450741026
#Sta/Elev= 30
       0  2651.6    37.7 2652.26    71.9 2650.86    89.4    2648   112.3 2641.86
   127.6 2635.64   169.1 2614.08     202 2593.71   243.5 2565.49   281.7 2535.11
   314.6 2513.03   352.1 2497.27   361.5 2491.65   371.5 2490.23   406.4 2493.95
   436.6 2493.81     446 2493.27   452.9 2489.17   456.5 2487.42   461.6 2489.08
   464.7 2491.21   484.9 2495.29   511.7    2510   553.9 2526.24   563.7 2528.05
   592.5 2541.59   666.5 2571.77   708.7 2585.41   788.5  2600.9   909.7 2610.23
#Mann= 5 ,-1,0
       0      .1       0     350     .06       0   452.9    .045       0
   461.6     .06       0     470      .1       0
#XS Ineff= 2 , 0
          427.04 2502.21
Permanent Ineff=
       F       F
Bank Sta=452.9,461.6
XS Rating Curve= 0 ,0
Exp/Cntr(USF)=0,0
Exp/Cntr=0.3,0.1