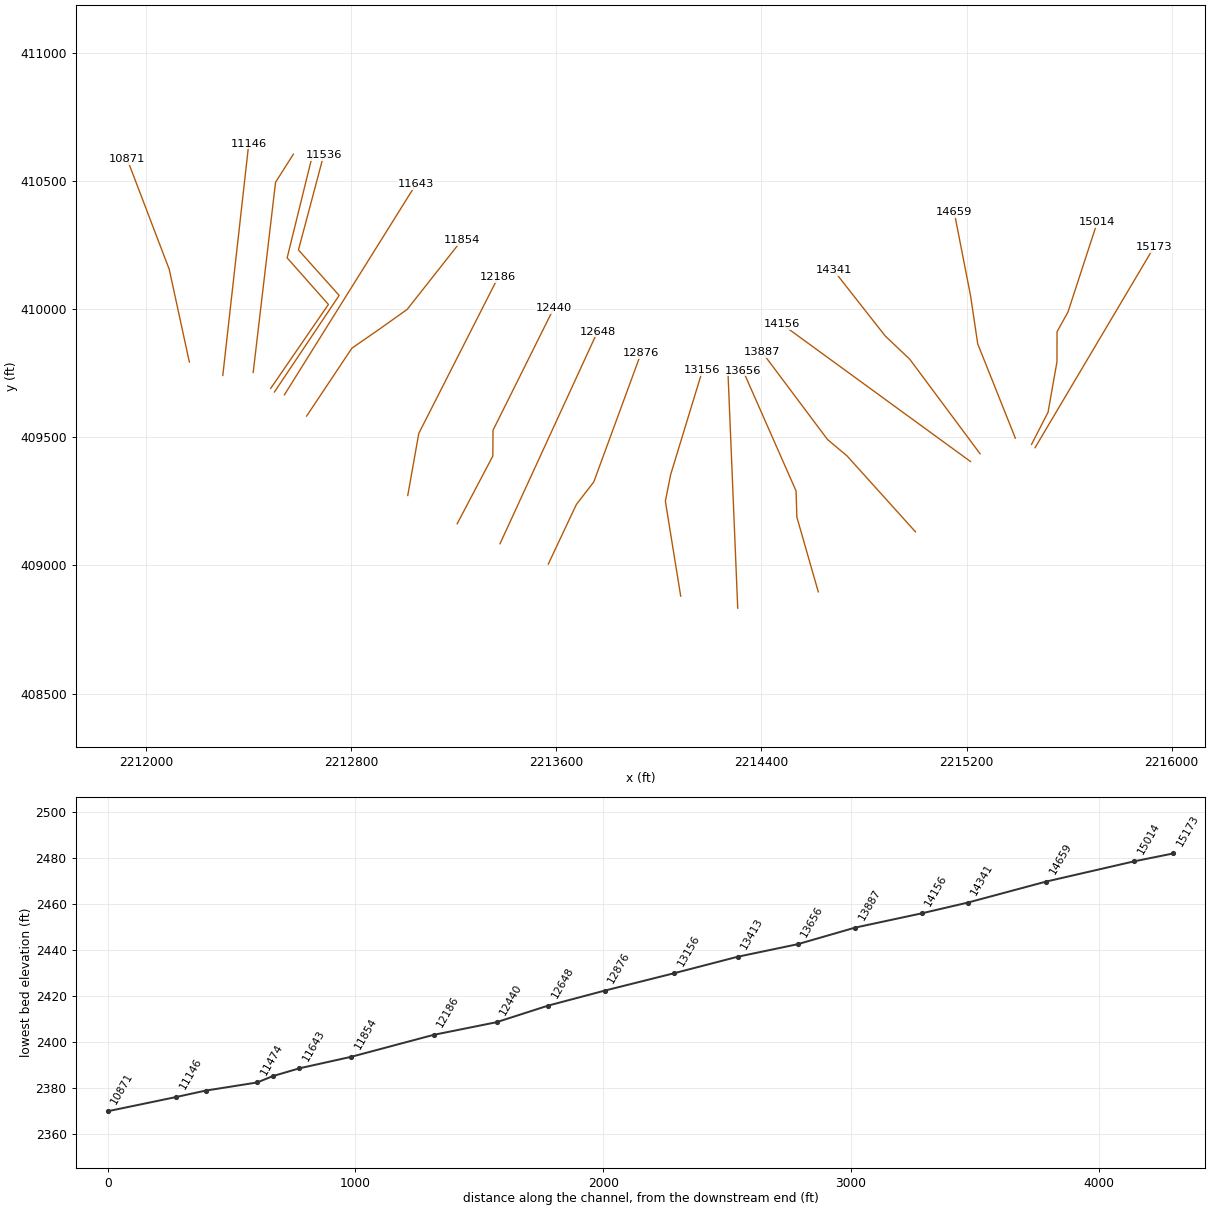
HEC-RAS study ISLNDLCKRN.prj: ISLNDLCKRN

--- ISLNDLCKRN.g01 (geometry) --- (continued)

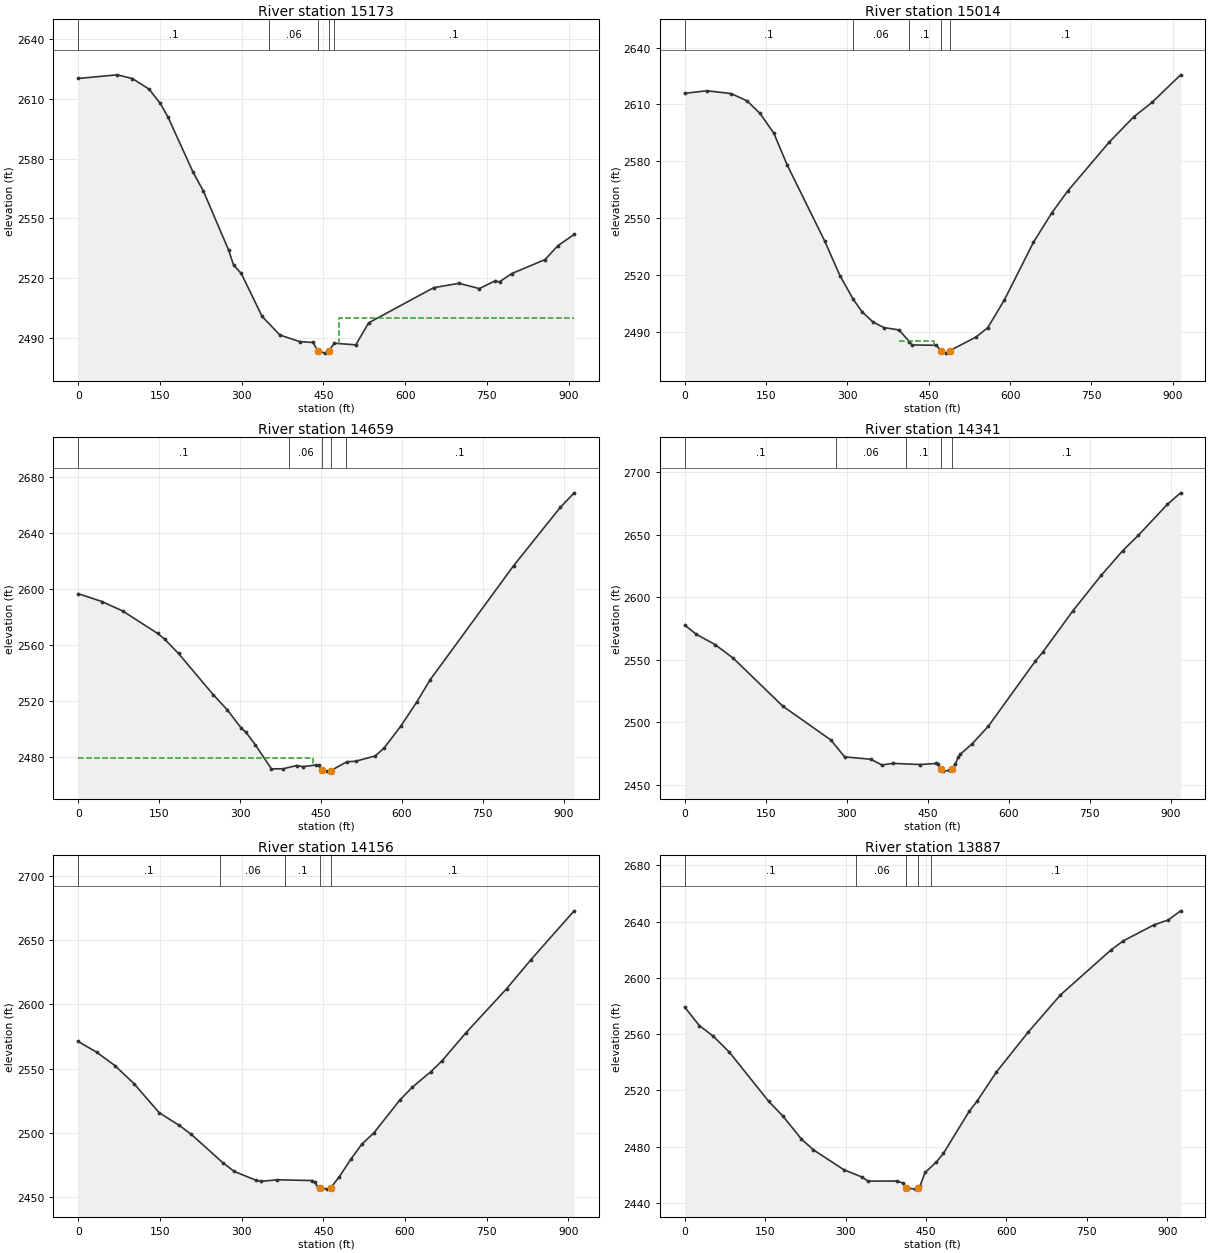
Type RM Length L Ch R = 1 ,15173   ,157.5,158,158.2
XS GIS Cut Line= 2
     2215467.469      409459.683     2215931.476       410242.85
#Sta/Elev= 30
       0 2620.31    71.5 2622.15    99.4 2620.29   130.1 2614.95   150.5 2607.78
   164.5 2601.07     211 2573.08   229.6 2563.76   276.1 2533.97   285.3 2526.35
   299.3 2522.24   337.4 2500.67   370.2 2491.27   406.2 2487.99   430.8 2487.51
440.05372483.264   452.7 2482.16     460 2483.27     470 2487.14   509.6 2486.33
     533 2497.38   652.6 2515.11   699.1 2517.27   736.3 2514.63   764.2  2518.4
   773.5 2518.05   795.7 2522.17   856.7 2529.19   880.7 2536.26   910.3 2541.85
#Mann= 5 ,-1,0
       0      .1       0     350     .06       0440.0537    .045       0
     460     .06       0     470      .1       0
#XS Ineff= 2 , 0
                          479.44         2499.74
Permanent Ineff=
       F       F
Bank Sta=440.0537,460
XS Rating Curve= 0 ,0
Exp/Cntr=0.3,0.1

Type RM Length L Ch R = 1 ,15014   ,345.8,355.7,363
XS GIS Cut Line= 6
2215453.72145466409472.6446802172215518.02791426409597.701961949
2215552.83018634409795.2560358572215553.06645521409911.953699187
2215595.67939314409988.9819368972215709.96771634410339.220346704
#Sta/Elev= 30
       0 2615.88    40.8 2617.23    85.4 2615.76   115.1 2611.88   138.9 2605.25
   164.5 2594.77   188.8 2578.18   257.9 2538.06   286.3 2519.64   310.7 2507.17
   326.9 2500.62   347.1 2495.18   367.1 2492.23   395.1 2490.98   414.3 2484.84
   419.1 2483.06     464 2482.87472.12192480.115   481.7 2478.73   489.1 2480.09
   537.6 2487.28   558.8 2492.18   589.2 2506.67   642.9 2537.17   676.6 2552.63
     706 2564.23   782.8 2590.14   828.1 2603.48   861.7 2611.09   914.4 2625.64
#Mann= 5 ,-1,0
       0      .1       0   310.7     .06       0   414.3      .1       0
472.1219    .045       0   489.1      .1       0
#XS Ineff= 1 ,-1
  396.07     460    2485
Permanent Ineff=
       F
Bank Sta=472.1219,489.1
XS Rating Curve= 0 ,0
Exp/Cntr(USF)=0,0
Exp/Cntr=0.3,0.1

Type RM Length L Ch R = 1 ,14659   ,312.5,317.5,330.2
XS GIS Cut Line= 4
 2215390.5285818409496.5389435682215243.70412251409864.860580033
2215216.06702409410051.155095325      2215151.99      410379.287
#Sta/Elev= 30
       0 2596.76    43.8 2591.13    82.4 2584.39   147.1 2568.35     160 2564.32
   185.9    2554   250.4  2524.5   276.3 2513.75   302.1 2500.69   310.7  2497.8
     328 2488.89   358.1 2471.58   379.6 2471.57   404.9 2473.94     417 2473.13
   441.3 2474.34   445.4 2473.96   452.7 2470.46   461.5 2469.92   468.7 2470.35
   497.9 2476.63   514.1 2476.98   550.5 2480.78   566.7 2486.35   597.7 2501.96
   627.7 2519.45   652.1  2535.1     807 2616.76   893.3 2658.34   919.2 2668.82
#Mann= 5 ,-1,0
       0      .1       0     390     .06       0   452.7    .045       0
   468.7     .06       0  496.51      .1       0
#XS Ineff= 2 , 0
           435.4 2479.12
Permanent Ineff=
       F       F
Bank Sta=452.7,468.7
XS Rating Curve= 0 ,0
Exp/Cntr=0.3,0.1

Type RM Length L Ch R = 1 ,14341   ,184.5,185.6,188.2
XS GIS Cut Line= 4
2215252.81442354409435.973921413 2214978.7682292409804.645931736
2214882.91350652409895.5850276162214681.37280754 410152.42652814
#Sta/Elev= 30
       0 2577.76    21.3 2570.43    56.3 2562.13    89.9 2551.21   181.4 2512.89
   270.6  2485.7   296.1 2472.16   344.4 2470.27   365.3 2465.67   385.3 2466.96
   435.9 2466.05     466  2466.9   468.5 2466.39     474 2462.48   478.6 2460.75
   489.9 2461.41     495 2462.59   501.2 2466.54   506.6 2472.35   509.7 2474.11
   532.3 2482.68   562.2 2496.81   648.7 2548.68     663 2556.17     719 2589.42
   770.9 2617.52   811.1 2637.49   839.6 2649.58   893.5 2674.47     918  2683.7
#Mann= 5 ,-1,0
       0      .1       0     280     .06       0     410      .1       0
     474    .045       0     495      .1       0
Bank Sta=474,495
XS Rating Curve= 0 ,0
Exp/Cntr(USF)=0,0
Exp/Cntr=0.3,0.1

Type RM Length L Ch R = 1 ,14156   ,268.7,268.2,266.2
XS GIS Cut Line= 2
     2215215.638      409405.501     2214479.886      409941.826
#Sta/Elev= 30
       0 2571.08      34  2562.7    67.4 2552.29   102.5 2538.21   148.8 2515.55
   185.5 2505.77   207.2 2498.88   265.6 2476.62   286.4 2469.91     326 2463.06
   335.9 2462.16   365.6 2463.37     430 2462.76     434 2461.53   440.3 2457.44
   444.8 2456.95   457.5 2456.09463.18482456.896   479.5 2465.82   500.4 2479.33
   520.4 2490.97   543.4 2500.19   590.2 2525.34   613.1 2535.37   647.8  2547.7
   667.6 2555.87   712.1 2578.01   786.4 2612.15   830.9 2634.67   910.5 2672.85
#Mann= 5 ,-1,0
       0      .1       0     260     .06       0     380      .1       0
   444.8    .045       0463.1848      .1       0
Bank Sta=444.8,463.1848
XS Rating Curve= 0 ,0
Exp/Cntr=0.3,0.1

Type RM Length L Ch R = 1 ,13887   ,237.4,231.5,223.9
XS GIS Cut Line= 4
2215000.88854982409131.2050595472214734.21579569409427.371574506
2214658.02358022409491.2747229622214402.41098639409832.910785861
#Sta/Elev= 30
       0 2579.29    27.4 2566.08    52.9 2558.74    83.4  2547.2   156.5 2512.34
   183.2 2501.77   217.2 2485.69   239.8 2477.88   296.5 2463.75     331 2458.41
   341.8 2455.59   395.6 2455.66   406.9 2454.26   413.52450.735   429.7  2449.9
   435.3 2450.57   438.7 2451.99   448.2 2461.72   469.1 2469.09   482.3 2475.25
   530.3 2505.08   545.3 2512.45   581.2 2533.11   640.2 2561.34   700.7 2587.93
   794.8 2619.85   817.9 2626.35     875 2637.68   901.7 2641.19   924.7 2647.68
#Mann= 5 ,-1,0
       0      .1       0     320     .06       0   413.5    .045       0
   435.3     .06       0  458.53      .1       0
Bank Sta=413.5,435.3
XS Rating Curve= 0 ,0
Exp/Cntr(USF)=0,0
Exp/Cntr=0.3,0.1

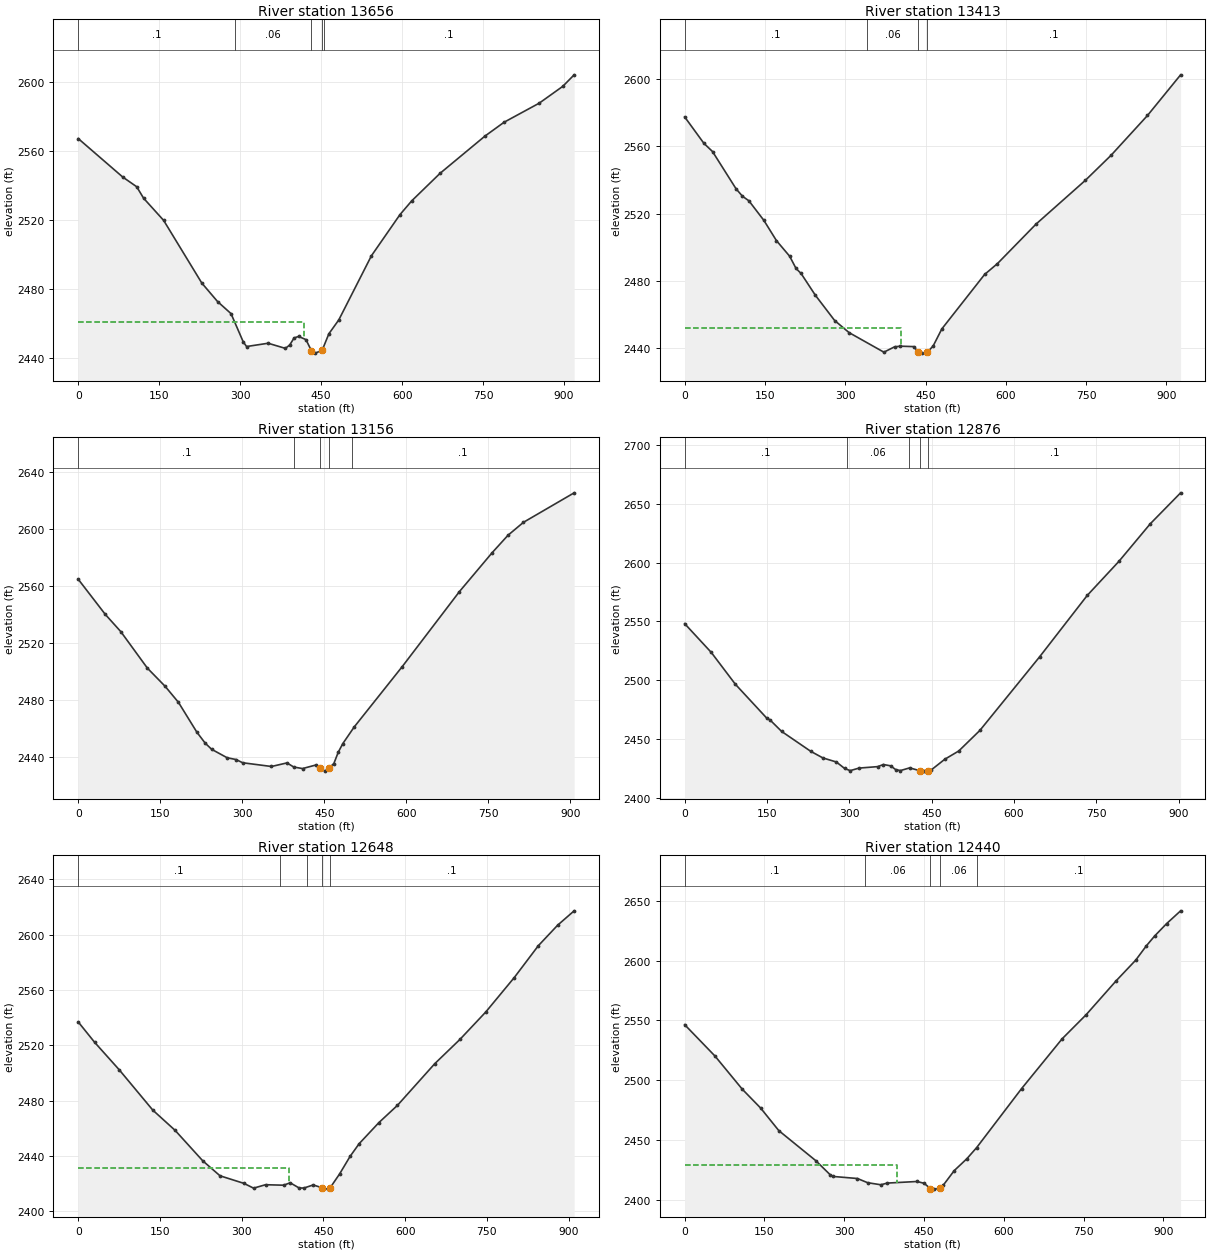
Type RM Length L Ch R = 1 ,13656   ,247.2,243.1,237.1
XS GIS Cut Line= 4
2214621.98149345408897.0362489082214538.44631462409188.263466801
 2214535.3755259409290.623090588      2214328.37       409760.43
#Sta/Elev= 30
       0  2567.3    82.4 2544.97   108.3 2539.32   121.2 2532.63   158.3 2519.76
     229 2483.38   258.1 2472.67   283.1 2465.64   305.7 2449.26   311.9 2446.53
   351.9 2448.44   383.8 2445.46   391.9 2447.45   399.9 2451.51   408.2 2452.39
   421.9 2450.56431.96642444.149   438.8  2442.7451.86642444.274   464.4 2453.95
   482.8 2462.01   543.2 2499.23   596.1 2523.13     618 2531.16   670.4 2547.11
   753.5 2568.71     789 2576.77     854 2587.83   897.7 2597.61   918.8  2604.3
#Mann= 5 ,-1,0
       0      .1       0     290     .06       0431.9664    .045       0
451.8664     .06       0  455.38      .1       0
#XS Ineff= 2 , 0
          417.46 2460.63
Permanent Ineff=
       F       F
Bank Sta=431.9664,451.8664
XS Rating Curve= 0 ,0
Exp/Cntr=0.3,0.1

Type RM Length L Ch R = 1 ,13413   ,259.2,256.5,253.2
XS GIS Cut Line= 2
2214307.78517041 408833.263457132214269.55251749409759.039838607
#Sta/Elev= 30
       0 2577.28    35.9 2561.62      52 2556.76      96 2534.66     108 2530.24
     120 2527.54     148 2515.92   171.5 2503.91   196.1 2494.69   208.1 2487.41
   217.5 2484.44   244.1 2471.57   280.2 2456.56   307.1  2449.4   372.2 2437.78
   392.2 2440.97   403.2 2441.34   428.3 2441.08   436.3 2437.73   444.3 2437.22
   453.2 2437.67   464.3  2441.5   480.5  2451.6   560.4 2483.87   584.4 2490.31
   656.5 2513.74   748.6 2539.67   796.6 2554.51   864.7 2578.13   926.6 2602.24
#Mann= 4 ,-1,0
       0      .1       0     340     .06       0   436.3    .045       0
   453.2      .1       0
#XS Ineff= 2 , 0
          403.38 2451.88
Permanent Ineff=
       F       F
Bank Sta=436.3,453.2
XS Rating Curve= 0 ,0
Exp/Cntr(USF)=0,0
Exp/Cntr=0.3,0.1

Type RM Length L Ch R = 1 ,13156   ,281.8,280.1,278.2
XS GIS Cut Line= 4
2214085.40795668408880.2506338592214025.62459944409250.702837311
 2214046.0965242409354.086057336     2214170.466      409761.762
#Sta/Elev= 30
       0 2564.95    49.6 2540.19    77.9 2528.11   126.5 2502.45     159 2489.66
   183.3 2478.41     217 2457.42   232.1 2449.77     244 2445.41   272.4 2439.45
   288.6 2438.21   300.8 2435.94   353.4 2433.32   381.8 2435.84   394.1 2432.95
   410.2 2431.86   434.9  2434.4442.81632431.931   451.2 2430.06 457.899 2432.04
   467.5 2435.42   475.6 2443.42   483.9 2449.43   504.8 2461.16   592.6 2503.56
   697.2  2556.3   757.2 2583.71     786 2595.88   814.2 2604.95   906.9 2625.68
#Mann= 5 ,-1,0
       0      .1       0  395.25     .06       0442.8163    .045       0
 457.899     .06       0  500.64      .1       0
Bank Sta=442.8163,457.899
XS Rating Curve= 0 ,0
Exp/Cntr=0.3,0.1

Type RM Length L Ch R = 1 ,12876   ,229.1,227.8,227.3
XS GIS Cut Line= 4
2213569.07569788409005.3103952812213678.31184908409237.437216595
2213746.58444359409326.1915894512213930.92044875409828.677885001
#Sta/Elev= 30
       0 2548.16    48.5 2523.62    92.4 2496.51   149.5 2467.68   155.5 2466.12
   176.7 2456.33   229.7 2439.39   251.8 2433.76   276.4 2430.29   291.5 2424.77
   301.6 2422.91   317.6 2425.08   351.8 2426.34   362.2 2428.13   375.2 2427.02
   384.5 2423.82     393 2422.95     410 2425.27   428.42422.883   435.6  2422.5
   443.42422.617   448.4 2423.17     474 2432.61   499.5 2439.67   537.9 2457.15
   646.8 2519.87   733.7 2572.25   791.3 2601.21   848.6  2633.3   903.8 2659.63
#Mann= 5 ,-1,0
       0      .1       0  296.55     .06       0  408.52      .1       0
   428.4    .045       0   443.4      .1       0
Bank Sta=428.4,443.4
XS Rating Curve= 0 ,0
Exp/Cntr(USF)=0,0
Exp/Cntr=0.3,0.1

Type RM Length L Ch R = 1 ,12648   ,208.8,208.5,208
XS GIS Cut Line= 2
     2213380.755      409084.758     2213760.714      409911.694
#Sta/Elev= 30
       0 2536.96      30 2522.26    75.3 2502.31   136.9 2473.14   177.8 2458.52
   228.5  2436.5   260.2 2425.65   304.2 2420.15   321.8  2416.7   343.8 2419.19
   376.9 2418.84     389 2420.58   405.5 2416.81   414.3  2416.8   431.2 2419.02
447.5754    2417   458.3    2416462.57462417.129   479.5 2426.88   498.8 2439.62
   515.5 2448.85   551.8 2464.13   585.9 2476.63   654.4 2506.78   700.4 2524.25
   747.9 2544.13   800.2 2569.04   844.4  2592.1     880 2606.99   910.1 2617.31
#Mann= 5 ,-1,0
       0      .1       0     370     .06       0     420      .1       0
447.5754    .045       0462.5746      .1       0
#XS Ineff= 2 , 0
          387.61 2431.11
Permanent Ineff=
       F       F
Bank Sta=447.5754,462.5746
XS Rating Curve= 0 ,0
Exp/Cntr=0.3,0.1

Type RM Length L Ch R = 1 ,12440   ,253.8,253.6,253.3
XS GIS Cut Line= 4
2213213.74907605409162.8054296822213352.73249876409426.986937053
2213353.47094697409527.5845987852213590.92292812410004.821178822
#Sta/Elev= 30
       0 2546.41    56.9 2520.18   108.3 2492.38   142.8 2476.62     177 2457.71
   246.4 2432.62   273.9 2420.63     279 2419.39   324.7 2417.67   343.8 2414.17
   368.7 2412.43   380.7 2413.83   436.6 2415.17   450.1 2413.65     462 2409.21
   467.8 2408.78   479.9 2409.45   485.9 2411.98   506.7 2424.29   530.5 2434.26
   548.9 2443.58   633.2 2492.86   709.6 2534.63   754.4 2554.64     811 2583.11
   847.7 2600.36   867.7 2612.33   883.4 2620.63   905.7  2630.9   932.2 2641.68
#Mann= 5 ,-1,0
       0      .1       0  338.51     .06       0     462    .045       0
   479.9     .06       0  549.11      .1       0
#XS Ineff= 2 , 0
             400  2429.2
Permanent Ineff=
       F       F
Bank Sta=462,479.9
XS Rating Curve= 0 ,0
Exp/Cntr(USF)=0,0
Exp/Cntr=0.3,0.1

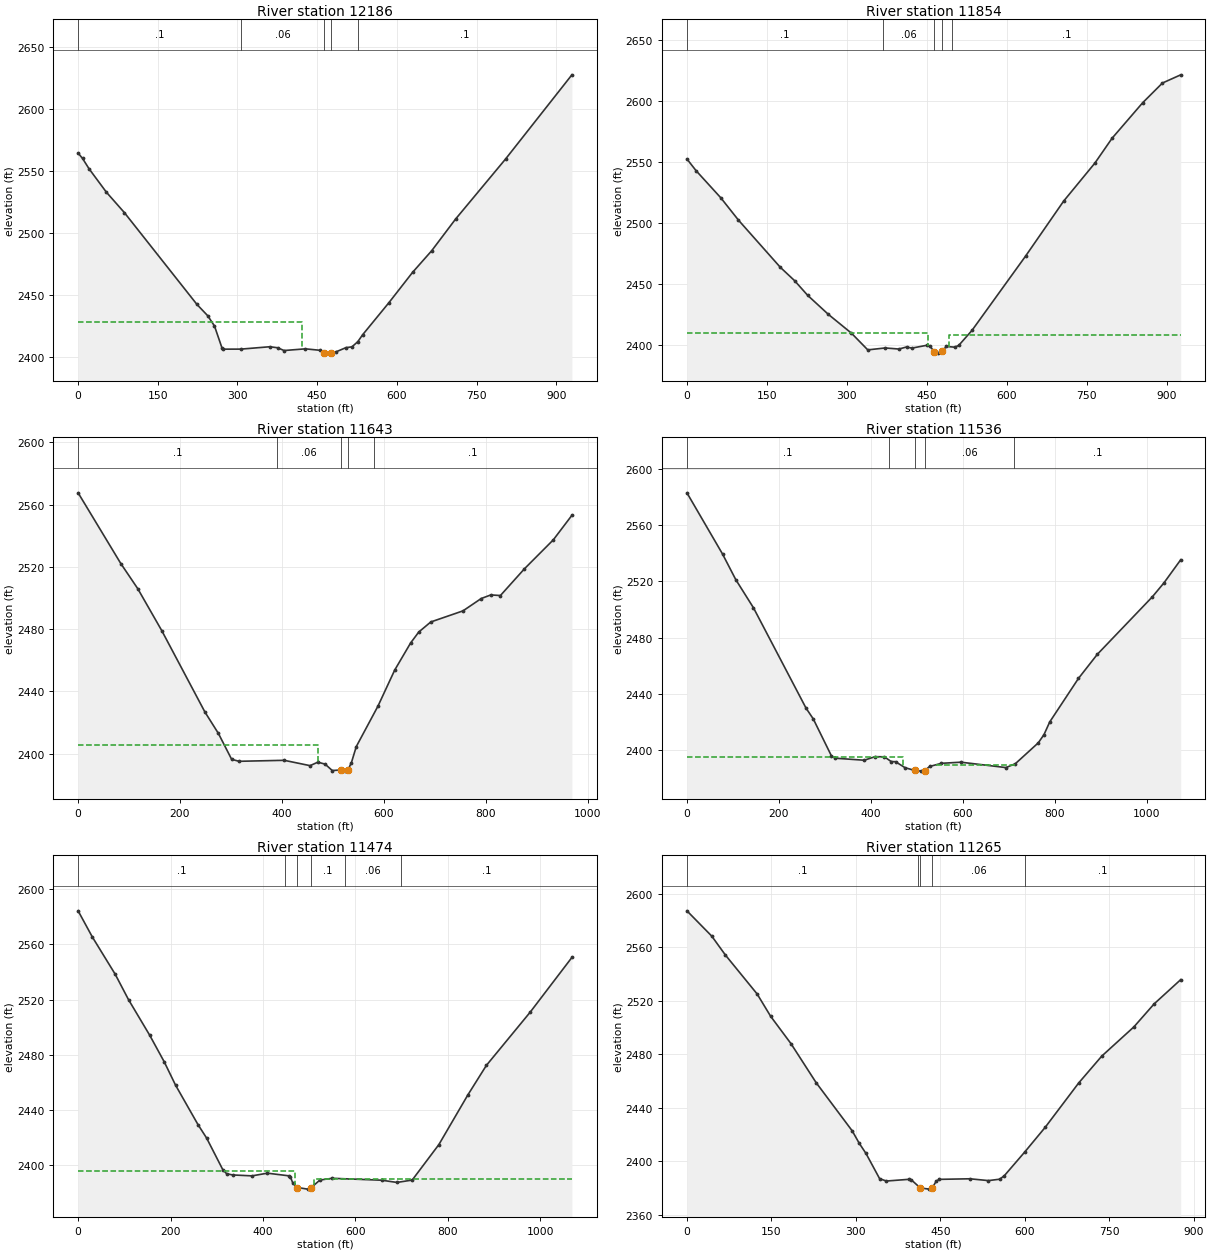
Type RM Length L Ch R = 1 ,12186   ,337.7,332.5,327.3
XS GIS Cut Line= 3
2213020.96124171409272.8888549752213064.00158636409515.298063336
      2213373.32      410124.452
#Sta/Elev= 30
       0 2564.66     8.4 2560.31    20.6 2552.01    53.1 2533.18      87 2516.69
   223.7 2442.56     244 2433.44   256.7 2425.15   270.7  2407.6   273.1 2406.49
   306.6 2406.53   360.8 2408.44   375.7 2407.62   387.6 2405.38   427.8 2406.75
   454.7  2405.6462.91712403.724   467.9 2403.29476.41712403.715   486.1 2404.44
     504 2407.69   515.5 2408.37   526.5 2412.57   535.4 2418.04   584.8 2443.88
   629.6 2468.49   665.5 2485.88   710.4  2511.4   804.6 2559.91   929.4 2627.79
#Mann= 5 ,-1,0
       0      .1       0   306.2     .06       0462.9171    .045       0
476.4171     .06       0   526.2      .1       0
#XS Ineff= 2 , 0
          420.89 2428.55
Permanent Ineff=
       F       F
Bank Sta=462.9171,476.4171
XS Rating Curve= 0 ,0
Exp/Cntr=0.3,0.1

Type RM Length L Ch R = 1 ,11854   ,202.6,210.3,214.3
XS GIS Cut Line= 5
2212626.55417949409582.8985829042212803.09985263409847.853299207
2212909.56243497409921.5286135272213018.79858617409999.359371262
2213231.80908103410269.718845499
#Sta/Elev= 30
       0 2552.66    17.2 2543.08    63.4 2520.96    96.7  2502.6   175.2 2463.98
   201.8 2453.12   226.5 2441.03   265.3 2425.46   308.6 2410.07   339.2 2396.41
   371.9 2397.98   397.5  2397.1   412.1 2398.81   421.8 2397.86   451.1 2400.26
     456 2399.23463.84762395.059   470.7 2393.75478.14762395.258   486.8 2399.22
   502.4 2398.61   509.7 2400.01   534.6 2412.31   635.2 2473.18   706.7 2518.25
   765.2 2549.31   797.5 2569.69   854.8  2598.7   891.9 2614.85   926.2 2621.56
#Mann= 5 ,-1,0
       0      .1       0  368.39     .06       0463.8476    .045       0
478.1476     .06       0  497.86      .1       0
#XS Ineff= 2 , 0
          452.39 2409.93  492.39         2408.95
Permanent Ineff=
       F       F
Bank Sta=463.8476,478.1476
XS Rating Curve= 0 ,0
Exp/Cntr(USF)=0,0
Exp/Cntr=0.3,0.1

Type RM Length L Ch R = 1 ,11643   ,83.3,107,120.7
BEGIN DESCRIPTION:
structure xs 4
END DESCRIPTION:
XS GIS Cut Line= 2
2212540.04458078409665.9866826832213053.42758078410488.199682683
#Sta/Elev= 30
       0 2567.59    83.9  2522.1   116.9 2506.09   164.1 2479.09     249 2426.67
   275.3    2413   301.4  2396.3   315.9 2395.04   404.6 2395.67   455.3 2392.24
   470.6 2394.47   484.8 2393.23   498.9 2389.11   516.3 2389.46   524.4 2388.72
  529.66  2389.5   536.5 2394.18   546.1 2404.53   588.5 2430.43   621.5 2453.68
   652.7 2471.09   668.7 2478.12   692.3 2484.59   755.5 2491.72   791.3 2499.66
   810.1 2501.97     829 2501.59   876.2 2518.78   932.8 2537.37   969.3 2553.13
#Mann= 5 ,-1,0
       0      .1       0     390     .06       0   516.3    .045       0
  529.66     .06       0     580      .1       0
#XS Ineff= 2 , 0
          471.06 2405.46
Permanent Ineff=
       F       F
Bank Sta=516.3,529.66
XS Rating Curve= 0 ,0
Exp/Cntr=0.5,0.3

Type RM Length L Ch R = 1 ,11536   ,65.5,62.4,79.3
BEGIN DESCRIPTION:
structure xs 3; 25.7 ft between structure & xs
END DESCRIPTION:
XS GIS Cut Line= 4
2212501.05909833 409676.924286062212753.41061317410053.798600803
2212594.72669117410231.2160413692212692.80217074410600.376554347
#Sta/Elev= 30
       0 2582.95    77.4  2539.5   106.2 2521.31   144.7 2501.29     259 2430.04
   274.7 2422.39   313.8  2396.4   322.5 2394.51   385.4 2393.07     409 2395.59
   429.2  2395.5   444.1 2392.13   453.6 2392.03   474.2 2387.77   495.7 2385.78
   509.4 2385.33   517.1 2385.77   527.6 2388.62   553.1 2390.87   595.6 2391.68
   693.6 2387.85     714 2390.58     764 2405.45   776.4  2411.3   788.8 2420.26
   851.3 2451.19   892.3 2468.28  1011.6 2508.99  1037.1 2518.99  1073.6 2535.43
#Mann= 5 ,-1,0
       0      .1       0     440     .06       0   495.7    .045       0
   517.1     .06       0  711.59      .1       0
#XS Ineff= 4 ,-1
       0     470 2395.55   542.6  648.12  2389.7  648.12  715.92 2389.95
  715.92  1073.6  2389.7
Permanent Ineff=
       F       F       F       F
Bank Sta=495.7,517.1
XS Rating Curve= 0 ,0
Exp/Cntr(USF)=0,0
Exp/Cntr=0.5,0.3

Type RM Length L Ch R = 1 ,11474   ,218,208.8,179.2
BEGIN DESCRIPTION:
structure xs 2; 14.1 ft between structure & xs
END DESCRIPTION:
XS GIS Cut Line= 4
2212486.73346648409691.2499179072212711.53568931410018.535507026
2212550.64782395410200.3608343142212653.13119024410616.906129555
#Sta/Elev= 30
       0 2584.39    30.8 2565.42    80.3 2538.41   109.1 2519.99   154.9 2494.22
   186.5 2474.84     211 2457.94   259.5 2429.37   278.1 2419.66   313.4 2396.56
   321.7 2393.72   334.6 2392.87   376.4 2392.21   409.8 2394.16   456.5 2392.22
   459.3 2391.65   464.7 2387.02   474.6 2383.77   496.7 2382.59   504.7 2383.77
   523.4 2389.18   550.1 2390.45   657.2 2389.05   690.1 2387.45   723.1 2389.15
   780.9 2414.91   843.4 2450.79   883.7 2472.31   978.5  2510.9  1068.8 2550.58
#Mann= 6 ,-1,0
       0      .1       0  447.05     .06       0   474.6    .045       0
   504.7      .1       0  577.05     .06       0  699.84      .1       0
#XS Ineff= 2 , 0
             470 2395.55     511          2389.7
Permanent Ineff=
       F       F
Bank Sta=474.6,504.7
XS Rating Curve= 0 ,0
Exp/Cntr(USF)=0,0
Exp/Cntr=0.5,0.3

Type RM Length L Ch R = 1 ,11265   ,119.3,119.4,119.4
BEGIN DESCRIPTION:
structure xs 1
END DESCRIPTION:
XS GIS Cut Line= 3
2212418.18073337409753.3530795822212505.37596845410495.144427272
 2212574.8794167410605.086245413
#Sta/Elev= 30
       0 2587.07    44.1 2568.15    68.3 2554.04   124.7 2524.91   148.8 2508.15
   184.7 2487.84   229.4 2458.67   293.6 2422.56   305.9 2413.39     318 2405.72
   342.2 2386.87   354.2 2385.09   394.5 2386.38   398.6 2385.95   414.7 2379.84
   430.8 2379.04   435.7 2379.98   442.9  2385.1   448.5 2386.35   502.6 2386.77
   535.5 2385.41   555.6 2386.47   563.9 2389.17     600 2406.81   636.2 2425.19
   695.8  2458.4   736.8 2478.49   793.9 2500.34   829.8 2517.52     877 2535.64
#Mann= 5 ,-1,0
       0      .1       0     410     .06       0   414.7    .045       0
   435.7     .06       0     600      .1       0
Bank Sta=414.7,435.7
XS Rating Curve= 0 ,0
Exp/Cntr(USF)=0,0
Exp/Cntr=0.3,0.1

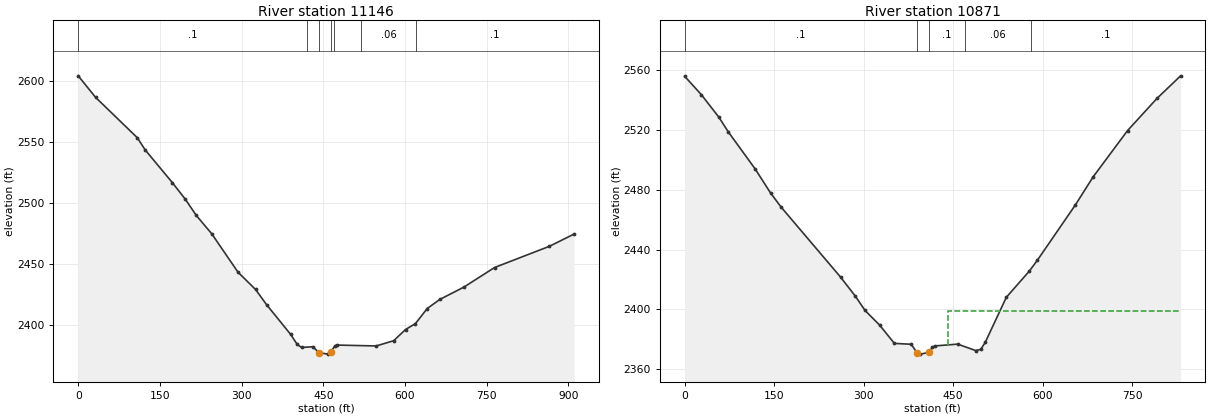
Type RM Length L Ch R = 1 ,11146   ,267.1,275.2,281.2
XS GIS Cut Line= 2
     2212299.673      409741.596     2212401.034      410646.483
#Sta/Elev= 30
       0 2604.32    31.8 2586.72   108.3 2553.67   123.1 2543.52   172.7 2516.86
   196.8 2503.09   216.5 2490.06   245.1  2474.9   293.4 2443.38   325.6 2429.22
   345.7 2416.83     390 2392.42   402.1 2384.17   410.1 2381.68   430.8  2382.3
   442.3 2377.38   458.4 2376.24   463.4 2377.71   470.6 2382.59   474.5 2383.68
     547 2382.94   579.2 2387.24   600.9 2396.41     619 2401.21   640.7 2413.59
   663.7 2421.03     708 2431.15   764.3 2447.21   865.2 2464.63   910.5 2474.66
#Mann= 7 ,-1,0
       0      .1       0     420     .06       0   442.3    .045       0
   463.4     .06       0     470      .1       0     520     .06       0
     620      .1       0
Bank Sta=442.3,463.4
XS Rating Curve= 0 ,0
Exp/Cntr=0.3,0.1

Type RM Length L Ch R = 1 ,10871   ,187.9,185.2,183.7
XS GIS Cut Line= 3
2212169.23201873409793.7914494732212090.88267706410155.209380375
2211926.60179938410586.130759527
#Sta/Elev= 30
       0 2556.06      28 2543.72    57.6 2528.51      73 2518.88   118.1 2494.04
   144.1 2477.83   161.8 2468.39   261.3 2421.59   285.9  2408.9   302.2 2399.32
   326.7 2389.48   351.4 2377.26   379.6 2376.69   389.3 2371.01   395.1 2370.08
     410  2371.3   414.7 2374.56     419 2375.56   457.5 2376.77   487.5 2372.49
   496.1 2373.23   503.6 2377.94   538.9 2408.09   577.4 2425.61   590.8 2432.82
   654.5 2469.84   684.4 2488.72   742.1 2519.72   791.8 2541.41     831 2556.36
#Mann= 5 ,-1,0
       0      .1       0   389.3    .045       0     410      .1       0
  469.81     .06       0  579.81      .1       0
#XS Ineff= 2 , 0
                          440.86          2398.8
Permanent Ineff=
       F       F
Bank Sta=389.3,410
XS Rating Curve= 0 ,0
Exp/Cntr(USF)=0,0
Exp/Cntr=0.3,0.1