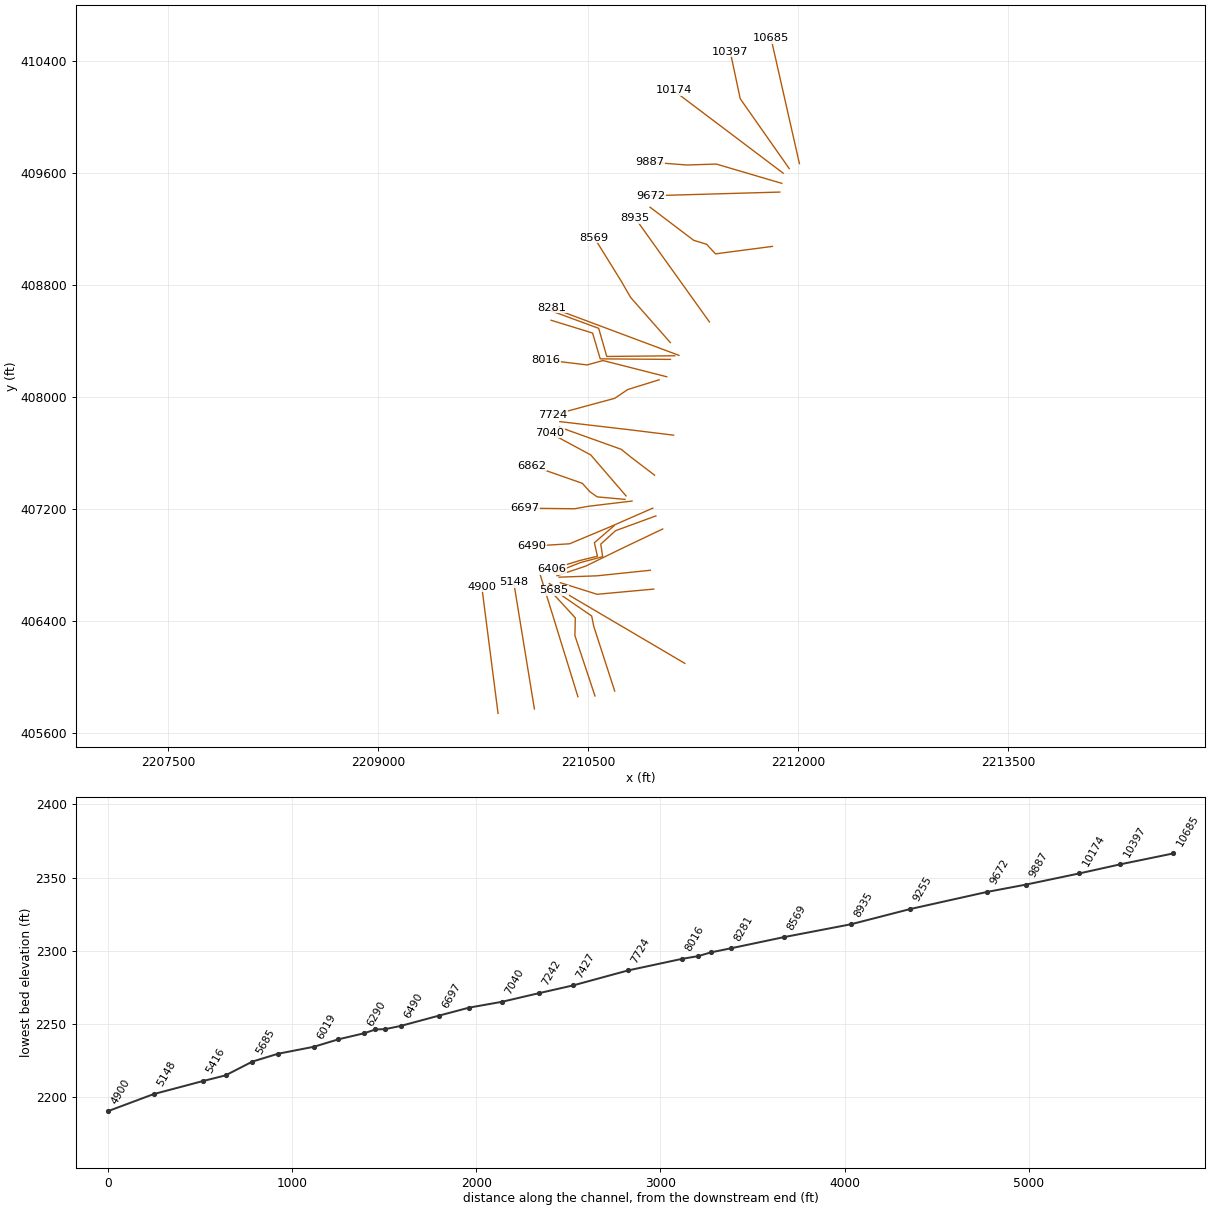
HEC-RAS study ISLNDLCKRN.prj: ISLNDLCKRN

--- ISLNDLCKRN.g01 (geometry) --- (continued)

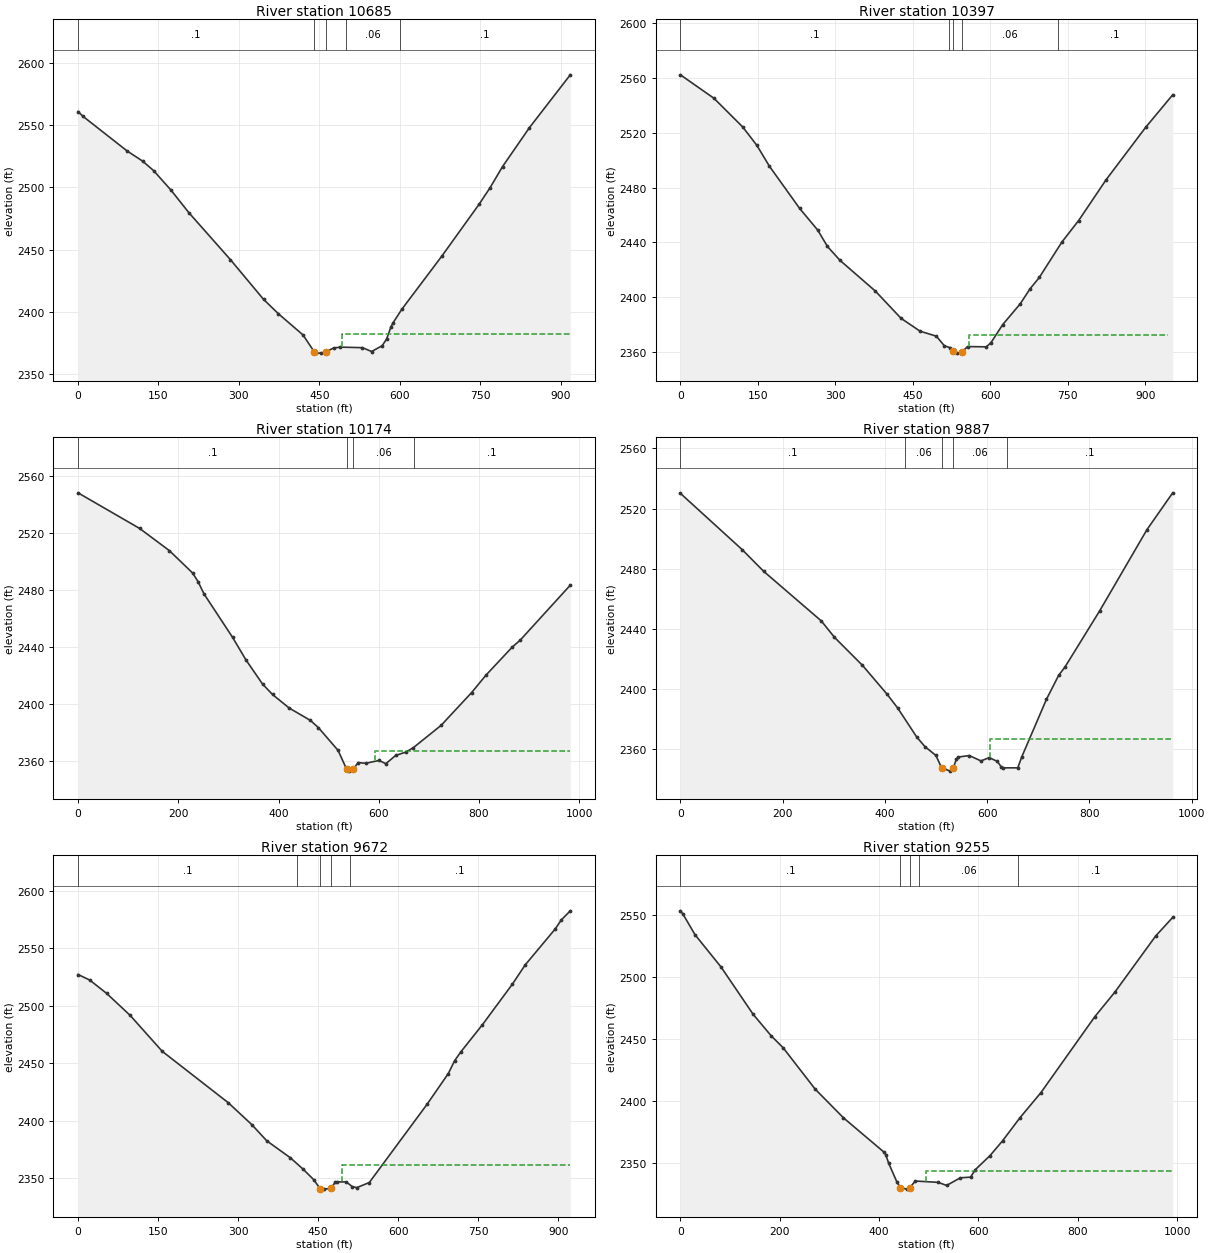
Type RM Length L Ch R = 1 ,10685   ,285.4,288.2,295.2
XS GIS Cut Line= 2
     2212009.874      409667.857     2211807.177      410563.231
#Sta/Elev= 30
       0 2561.09     9.6  2557.1    91.6 2529.33   120.3 2521.23   140.8 2513.59
   173.6 2497.69   206.5 2479.76   284.3 2441.79   345.9  2409.9   373.7 2398.28
   419.7 2381.16   440.6 2367.59   444.3 2366.59   452.5 2366.57   462.32367.597
   476.6 2370.71   489.4  2371.4   530.4 2370.96   547.6 2367.86   567.3  2372.6
   575.5 2377.97   583.7 2387.81   587.8 2391.21   604.2  2402.1   678.1 2444.47
   747.8 2486.35   768.3 2499.67   791.7 2516.79   841.9 2548.16     918 2590.65
#Mann= 5 ,-1,0
       0      .1       0   440.6    .045       0   462.3      .1       0
     500     .06       0     600      .1       0
#XS Ineff= 2 , 0
                          492.96         2381.93
Permanent Ineff=
       F       F
Bank Sta=440.6,462.3
XS Rating Curve= 0 ,0
Exp/Cntr=0.3,0.1

Type RM Length L Ch R = 1 ,10397   ,220.1,223.4,227.2
XS GIS Cut Line= 3
2211937.36068923409632.0528128292211587.14200352410131.775359287
2211516.03014952410467.302358236
#Sta/Elev= 30
       0 2562.38    64.9 2545.25   120.6 2524.31   147.9 2510.92   172.3 2495.63
   230.9 2464.78   265.9 2448.97   284.7 2437.02   308.9 2426.91   377.5 2404.43
   427.2 2384.55     464 2375.16   495.6  2371.5   510.9 2364.56   521.5 2363.17
   527.2 2360.51   535.8 2359.13   545.7 2360.17   555.9 2363.91   592.4 2363.73
   601.5 2366.87     624 2379.94   657.8 2395.05   677.1 2406.14   694.9 2414.38
   738.7 2440.27   771.1 2455.97   824.3 2485.76   900.7 2523.95   953.2 2547.78
#Mann= 5 ,-1,0
       0      .1       0     520     .06       0   527.2    .045       0
   545.7     .06       0  730.23      .1       0
#XS Ineff= 1 ,-1
  558.87   944.6 2372.65
Permanent Ineff=
       F
Bank Sta=527.2,545.7
XS Rating Curve= 0 ,0
Exp/Cntr(USF)=0,0
Exp/Cntr=0.3,0.1

Type RM Length L Ch R = 1 ,10174   ,278,287.1,295.2
XS GIS Cut Line= 2
      2211894.26      409599.379     2211110.487      410191.155
#Sta/Elev= 30
       0 2548.15   122.9 2523.16   182.2 2507.61   228.7 2491.88   239.8 2485.67
   251.2  2477.3   308.4 2446.72   334.9 2430.99   368.3 2413.92     388 2406.66
   421.2 2397.17   463.7 2388.47   479.7 2383.36   518.9 2367.41535.78452354.283
   539.7 2352.89   548.9 2354.29     559 2358.87     574 2358.38   600.4 2360.38
   614.1 2358.12   633.9 2363.94   654.2 2366.26   669.2 2369.41   724.4    2385
   785.3 2408.03   813.8 2420.19     866  2439.8   882.4 2444.87   982.1 2483.35
#Mann= 4 ,-1,0
       0      .1       0535.7845    .045       0   548.9     .06       0
     670      .1       0
#XS Ineff= 2 , 0
                          592.68         2366.81
Permanent Ineff=
       F       F
Bank Sta=535.7845,548.9
XS Rating Curve= 0 ,0
Exp/Cntr=0.3,0.1

Type RM Length L Ch R = 1 ,9887    ,214.4,214.4,214.6
XS GIS Cut Line= 4
2211884.10806551409526.9130172932211415.75806721409664.823658191
2211206.84392803409657.9963987412210941.94626136409678.478177092
#Sta/Elev= 30
       0 2530.08   120.9 2492.62   162.8 2478.24   275.6 2445.22   301.3 2434.34
   356.1 2415.69   404.4 2396.42   425.3 2387.14   462.4 2367.92   478.5 2361.56
   499.8 2355.75   510.7 2347.63   527.8 2345.33   533.7 2347.58   539.8 2353.22
   543.8 2354.71     565  2355.7   587.9 2352.12   603.9 2354.31   619.9 2351.81
   627.9 2347.98   631.9 2347.51   659.9 2347.52   667.9 2354.98     716 2393.13
   739.9 2409.07   752.1 2414.52   820.3 2452.07   912.6 2505.97   962.9 2530.44
#Mann= 5 ,-1,0
       0      .1       0     440     .06       0   510.7    .045       0
   533.7     .06       0  638.23      .1       0
#XS Ineff= 2 , 0
                          605.07         2366.87
Permanent Ineff=
       F       F
Bank Sta=510.7,533.7
XS Rating Curve= 0 ,0
Exp/Cntr(USF)=0,0
Exp/Cntr=0.3,0.1

Type RM Length L Ch R = 1 ,9672    ,427.5,417,404.6
XS GIS Cut Line= 2
      2211869.88      409464.561     2210947.691      409438.245
#Sta/Elev= 30
       0 2527.11    21.7 2522.35    53.7 2510.64    97.7 2491.52   157.8 2460.24
   281.8  2415.4   325.8 2396.36   353.8 2382.29   397.9 2367.57   421.9 2357.62
   441.9 2348.39   453.9 2340.52   461.9 2340.25   473.9 2340.95   481.9 2346.11
   485.9 2346.55   502.9 2346.52   513.9 2342.47   522.4 2341.54   545.9    2346
     654 2414.01     694 2440.87     706  2452.2     718 2460.06     758 2483.43
   814.2 2518.78     838 2535.41   894.1 2566.62   906.1 2574.76   922.6 2582.55
#Mann= 5 ,-1,0
       0      .1       0     410     .06       0   453.9    .045       0
   473.9     .06       0     510      .1       0
#XS Ineff= 2 , 0
                          495.21         2361.24
Permanent Ineff=
       F       F
Bank Sta=453.9,473.9
XS Rating Curve= 0 ,0
Exp/Cntr=0.3,0.1

Type RM Length L Ch R = 1 ,9255    ,322.2,320.2,318.7
XS GIS Cut Line= 5
 2211817.2009229409076.3138935652211410.29625965409023.061269852
2211347.48547271409091.3338643562211254.63474418409120.008354048
2210943.31171325409356.231531032
#Sta/Elev= 30
       0 2553.61     5.1    2551    29.3 2534.33    81.7 2508.21   146.4 2469.94
   182.6 2452.58   206.8 2442.87   271.3 2409.42   328.3 2386.21   410.4  2358.3
   413.3 2356.56     419 2349.78     436  2334.2     443 2329.76   455.8 2328.57
   461.82329.769   472.8 2335.12   519.2 2334.04   535.9 2331.53   563.6 2337.74
   584.1 2338.26   593.6 2344.25   623.5 2355.76   648.6 2367.66   683.7 2386.33
   725.7 2406.56   834.4 2468.05   874.6 2487.84   956.9 2533.28   991.1 2548.27
#Mann= 5 ,-1,0
       0      .1       0     443    .045       0   461.8      .1       0
  480.37     .06       0  680.32      .1       0
#XS Ineff= 2 , 0
                          495.21         2343.56
Permanent Ineff=
       F       F
Bank Sta=443,461.8
XS Rating Curve= 0 ,0
Exp/Cntr(USF)=0,0
Exp/Cntr=0.3,0.1

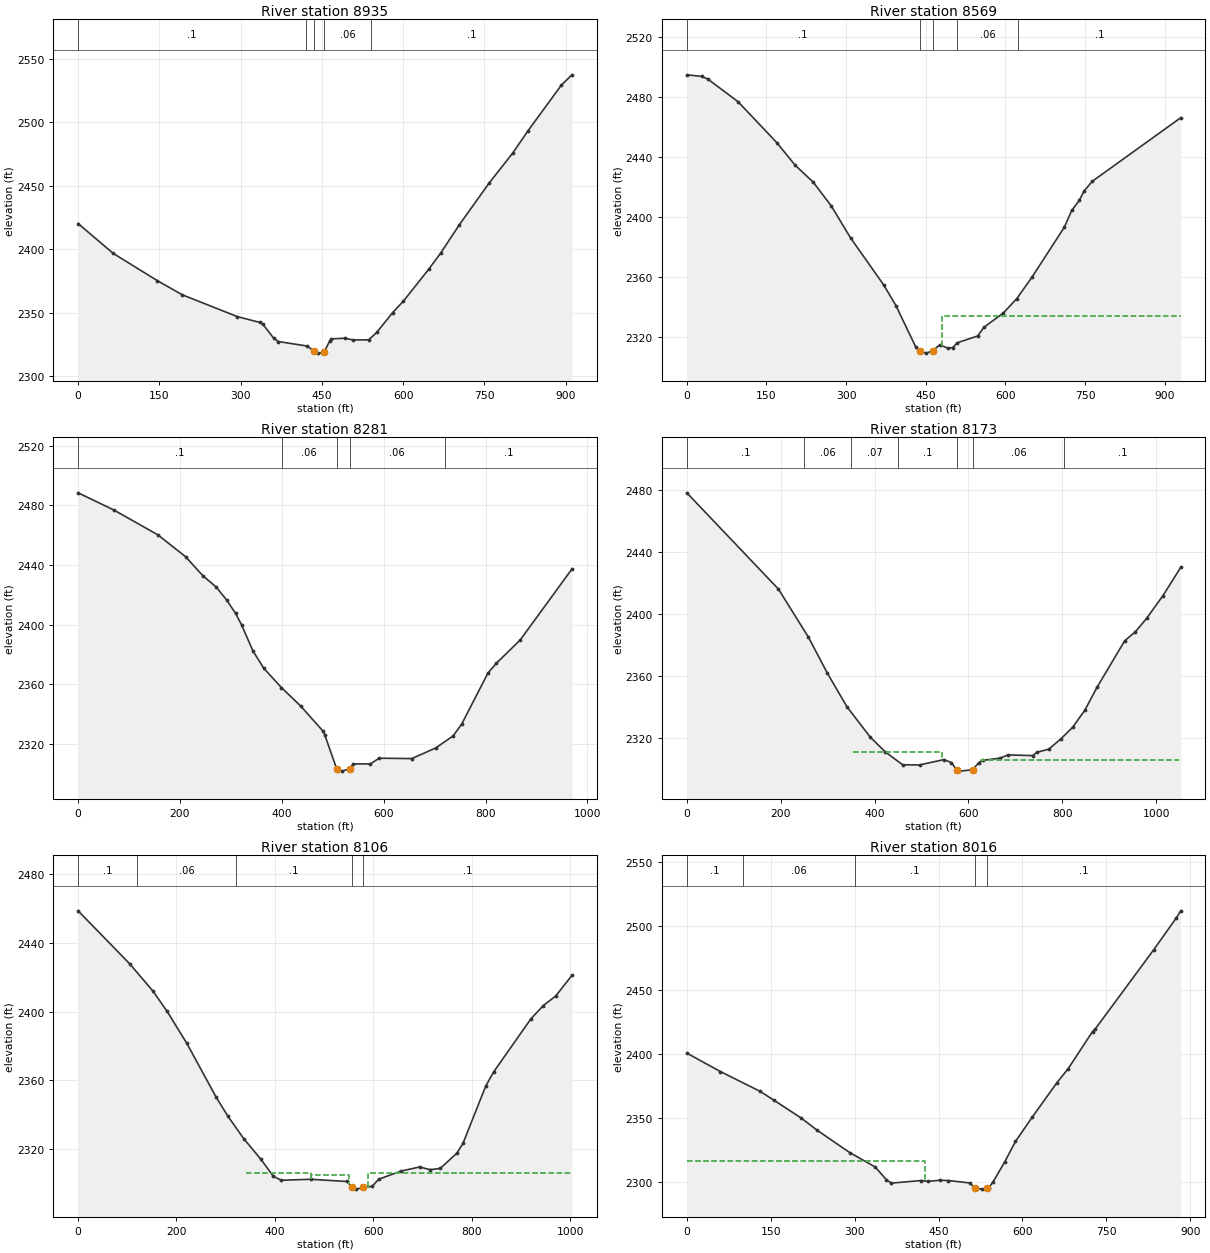
Type RM Length L Ch R = 1 ,8935    ,365.8,366,363.1
XS GIS Cut Line= 2
2211367.18716345408536.6594898882210836.77716345409278.453489889
#Sta/Elev= 30
       0 2420.25    64.6 2396.82   145.9 2375.38   192.4 2364.14     294 2346.98
   335.3 2342.41   340.9 2341.17   360.9 2330.06   369.5 2327.35   423.5 2323.78
   435.5 2319.59   443.2 2318.22   452.7 2318.48   454.62319.362   464.2 2327.48
   467.8 2329.44   492.8 2329.97   507.1  2328.6   536.6  2328.7   551.4 2334.53
   580.9 2350.21   600.6 2359.15   647.7 2384.48   669.4    2397   703.8 2419.26
   759.5  2452.5   802.5 2475.78   830.4 2493.13   892.3 2529.27   911.9 2537.36
#Mann= 5 ,-1,0
       0      .1       0     420     .06       0   435.5    .045       0
   454.6     .06       0     540      .1       0
Bank Sta=435.5,454.6
XS Rating Curve= 0 ,0
Exp/Cntr=0.3,0.1

Type RM Length L Ch R = 1 ,8569    ,275.6,288,298.6
XS GIS Cut Line= 4
  2211087.932154408389.204931618 2210804.4370349408711.641685008
2210737.46209317408827.9665838122210544.35543083409139.578950017
#Sta/Elev= 30
       0 2494.93    28.2 2493.85    39.5  2492.1    96.2  2477.1   169.3 2449.78
   203.9 2434.72   237.9 2423.45   271.6 2407.76   308.7 2386.04   371.1  2354.7
   393.8  2341.1   431.1 2313.53438.22662310.558   451.2 2309.39463.47462311.059
   476.3 2314.93   491.1  2312.8   500.4    2313   509.7 2316.35   547.8 2320.84
   559.5  2326.6   596.4 2336.24   621.5 2345.76     650    2360   710.7 2393.17
     725 2404.55   739.1 2411.18   748.4 2417.52   763.4 2423.88   930.2 2466.32
#Mann= 5 ,-1,0
       0      .1       0438.2266    .045       0463.4746      .1       0
  509.34     .06       0  623.57      .1       0
#XS Ineff= 2 , 0
                           480.8         2334.25
Permanent Ineff=
       F       F
Bank Sta=438.2266,463.4746
XS Rating Curve= 0 ,0
Exp/Cntr=0.3,0.1

Type RM Length L Ch R = 1 ,8281    ,123,108.5,86.6
BEGIN DESCRIPTION:
structure xs 4
END DESCRIPTION:
XS GIS Cut Line= 2
      2211149.75       408297.64     2210241.487      408637.402
#Sta/Elev= 30
       0 2488.49      70    2477   156.3 2460.36   210.9 2445.67   245.1 2432.83
   271.3 2425.22   292.1 2416.36   309.2 2407.58     321 2399.89   343.3 2382.41
   364.5  2370.8   399.2 2357.82   437.3 2345.36     480 2328.93   484.3 2326.07
   507.5 2303.47   510.6 2302.03   518.4 2301.77  533.272303.408   539.8 2306.59
     574 2306.63     591 2310.43   655.1 2310.19   702.1  2317.3   736.2 2325.39
     753 2333.23   804.6 2367.53   821.4  2374.2     868 2389.76   969.7 2437.46
#Mann= 5 ,-1,0
       0      .1       0     400     .06       0   507.5    .045       0
  533.27     .06       0     720      .1       0
Bank Sta=507.5,533.27
XS Rating Curve= 0 ,0
Exp/Cntr=0.5,0.3

Type RM Length L Ch R = 1 ,8173    ,62.2,66.5,69.9
BEGIN DESCRIPTION:
structure xs 3; 18.5 ft between structure & xs
END DESCRIPTION:
XS GIS Cut Line= 4
2211119.25705492 408294.760250552210634.12400588408289.695952663
2210576.48353476408490.7766735932210240.31885041408614.560264237
#Sta/Elev= 30
       0 2477.92   195.1 2416.07   259.1 2385.14   299.1 2362.19   341.1 2340.43
   391.1 2320.77   423.1  2311.3   459.9 2303.06     496 2302.94   547.8 2306.39
   563.7 2304.51574.87552299.885   580.7 2298.97609.17562299.807   621.9 2304.39
   630.3 2305.92   668.2 2307.33   684.4 2309.42   737.3 2308.94   745.8 2311.04
   771.4  2313.1     797 2319.65   822.5 2327.25   848.1 2338.07     874 2352.76
   933.2 2382.77     956 2388.58     980 2397.25  1014.4 2411.65  1052.6    2430
#Mann= 7 ,-1,0
       0      .1       0     250     .06       0     350     .07       0
     450      .1       0574.8755    .045       0609.1756     .06       0
  804.34      .1       0
#XS Ineff= 3 ,-1
  354.25     544 2311.09     544   556.4  2304.8   627.5  1048.6 2305.96
Permanent Ineff=
       F       F       F
Bank Sta=574.8755,609.1756
XS Rating Curve= 0 ,0
Exp/Cntr(USF)=0,0
Exp/Cntr=0.5,0.3

Type RM Length L Ch R = 1 ,8106    ,74.8,90.3,119.9
BEGIN DESCRIPTION:
structure xs 2; 23.7 ft between structure & xs
END DESCRIPTION:
XS GIS Cut Line= 4
2211088.99981955408268.8972532242210587.49211729408272.712924426
2210532.93767689 408457.041635712210236.50729483408548.505285194
#Sta/Elev= 30
       0 2458.79   104.8 2427.91     152 2412.03   180.8 2400.21   220.8 2381.62
   280.8 2350.01   304.8 2338.87   336.8 2325.87   371.4 2313.96   396.8 2304.01
   412.8 2301.67   472.8 2302.23   546.4 2300.94557.64672297.521   565.7 2296.49
579.5467 2297.53   597.8 2298.11   610.8 2302.24   656.4 2306.99   694.2 2309.41
   715.5 2307.85   736.1 2308.56   769.9 2317.43   782.5 2323.25   828.8  2356.7
   844.8 2364.87   920.6 2395.86   945.7 2403.54   970.8 2409.09    1004 2421.19
#Mann= 5 ,-1,0
       0      .1       0     120     .06       0     320      .1       0
557.6467    .045       0579.5467      .1       0
#XS Ineff= 3 ,-1
  342.04  472.94 2306.02  472.94   551.2  2304.8   589.1  1005.5 2305.96
Permanent Ineff=
       F       F       F
Bank Sta=557.6467,579.5467
XS Rating Curve= 0 ,0
Exp/Cntr(USF)=0,0
Exp/Cntr=0.5,0.3

Type RM Length L Ch R = 1 ,8016    ,291,291.5,299.3
BEGIN DESCRIPTION:
structure xs 1
END DESCRIPTION:
XS GIS Cut Line= 4
2211062.42123966408144.7674963312210607.34461071 408260.62416104
2210493.57545348408229.3115489562210200.28065363408264.799175984
#Sta/Elev= 30
       0 2400.66    60.1 2386.25   130.3 2370.99     155 2364.14   204.6 2349.98
   233.5 2340.33   291.2 2323.08   336.7 2311.88   356.9 2301.86   365.5 2299.24
   419.2 2301.27   431.6 2300.58   452.2  2301.5   467.7 2301.25   506.1 2299.36
     515 2295.37     527 2294.56   536.8  2295.2     540 2295.63   547.6 2300.27
   568.3 2315.77   587.6 2331.75   617.2 2350.52   661.5 2377.48   681.7 2388.45
   725.3 2417.46     730 2419.37   834.8 2481.33   875.1 2506.09     883 2511.64
#Mann= 5 ,-1,0
       0      .1       0     100     .06       0     300      .1       0
     515    .045       0   536.8      .1       0
#XS Ineff= 2 , 0
          426.48 2316.81
Permanent Ineff=
       F       F
Bank Sta=515,536.8
XS Rating Curve= 0 ,0
Exp/Cntr(USF)=0,0
Exp/Cntr=0.3,0.1

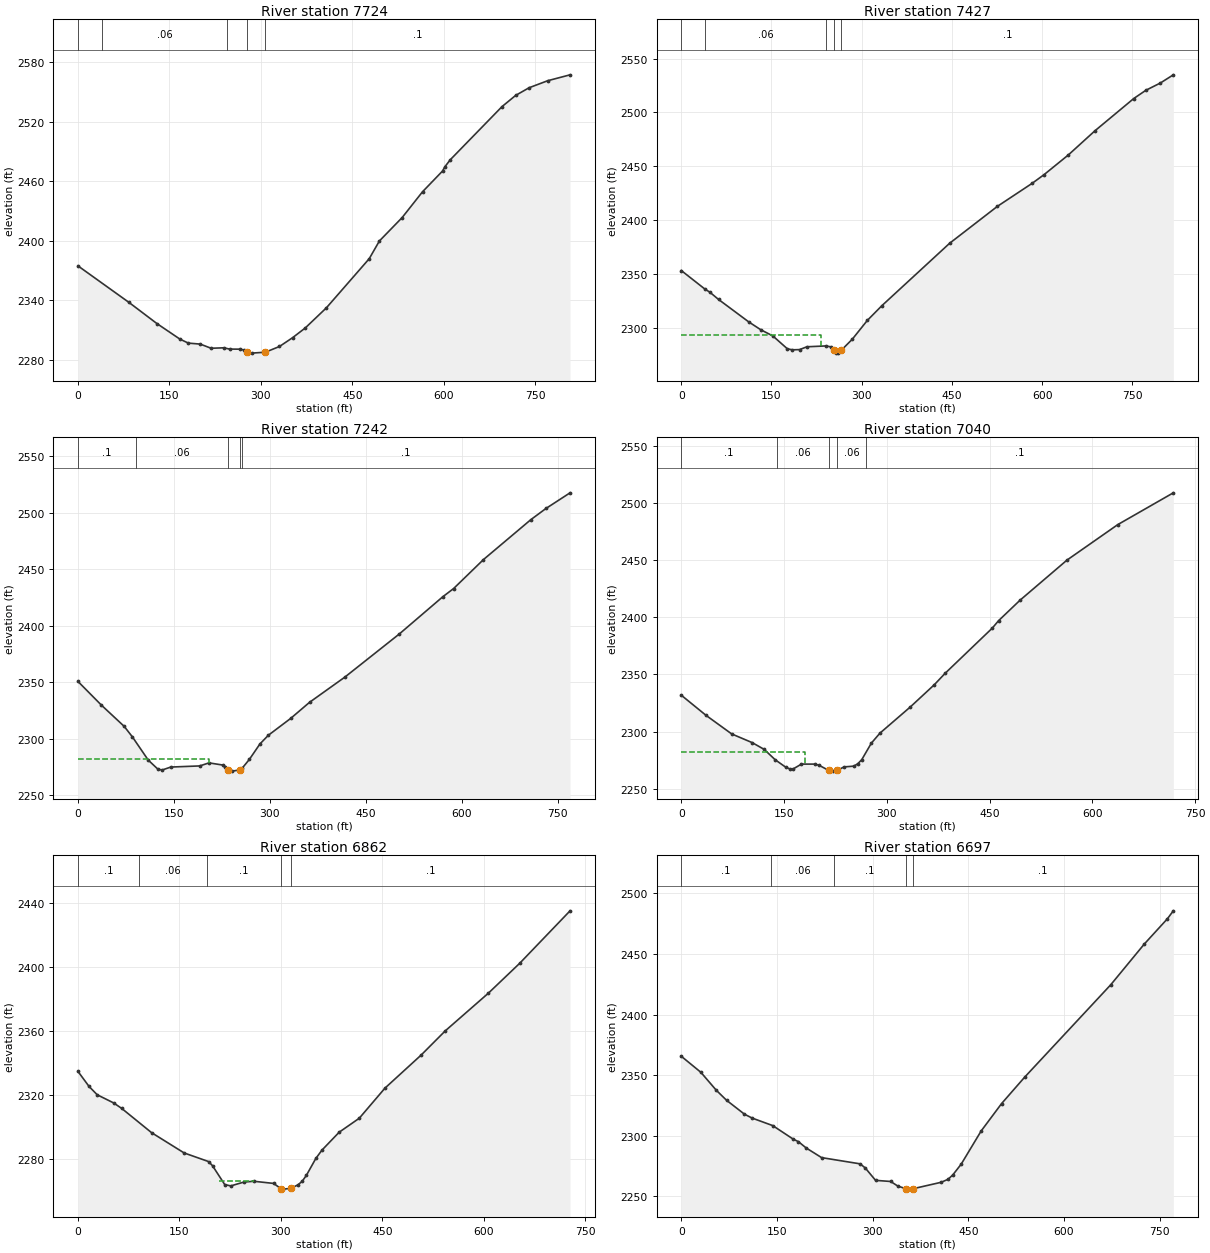
Type RM Length L Ch R = 1 ,7724    ,305.8,297.9,288.9
XS GIS Cut Line= 4
2211007.77923413 408122.924575492210783.57163359408053.240441221
2210690.90622439407990.5934040182210246.08270678407870.411586434
#Sta/Elev= 30
       0 2374.67    83.4 2337.94   129.4 2316.55   167.2 2300.83   181.1 2296.78
   200.6  2295.8   218.4  2291.6   238.9 2292.05   248.8 2290.77   266.1 2290.68
   272.7 2289.82   277.7 2287.89   284.9 2286.69307.55732287.634   330.6  2293.4
   352.1 2302.26   372.9 2312.07   407.5 2332.34   477.9 2381.98   494.5  2399.8
   531.8 2423.38   565.3 2449.44   598.1 2470.35   602.2 2474.84     611 2481.86
   695.8 2535.39   718.2 2546.68   740.2 2554.39   770.8 2561.49   807.4 2567.42
#Mann= 5 ,-1,0
       0      .1       0      40     .06       0  244.79      .1       0
   277.7    .045       0307.5573      .1       0
Bank Sta=277.7,307.5573
XS Rating Curve= 0 ,0
Exp/Cntr=0.3,0.1

Type RM Length L Ch R = 1 ,7427    ,190.9,184.7,177.9
XS GIS Cut Line= 3
2211111.26229573407727.247426162 2210812.2283318407764.114627195
2210298.81842113407824.194510358
#Sta/Elev= 30
       0 2353.18    39.4  2335.9    47.4 2333.12    61.9 2326.36   111.9  2305.6
   132.1 2298.22   152.2 2292.47   176.4 2280.52   184.5 2279.56   196.6 2279.76
     209 2282.39   240.4 2283.16     249 2282.32   254.2 2279.11     257 2276.92
     261 2276.49   266.4 2279.34   284.4 2289.41   309.4 2306.88   333.6 2320.55
   446.3  2378.5   525.8  2412.8   583.3 2434.06   603.4 2442.23   643.7 2460.49
   687.8 2482.86   752.4 2512.84   772.5 2520.48   796.7 2527.26   818.2 2534.85
#Mann= 5 ,-1,0
       0      .1       0      40     .06       0     240      .1       0
   254.2    .045       0   266.4      .1       0
#XS Ineff= 2 , 0
          232.11 2293.56
Permanent Ineff=
       F       F
Bank Sta=254.2,266.4
XS Rating Curve= 0 ,0
Exp/Cntr(USF)=0,0
Exp/Cntr=0.3,0.1

Type RM Length L Ch R = 1 ,7242    ,204.6,201.9,199.4
XS GIS Cut Line= 4
2210975.61883015  407441.4423243 2210810.9448314407566.908228112
2210737.00956665407626.2804861662210296.75867203407784.233097214
#Sta/Elev= 30
       0 2350.57    36.5 2329.67    72.2 2310.85      85 2301.56   109.9 2280.94
     125 2272.93   131.6 2272.21   145.1 2274.82   190.4 2275.81   204.9 2278.51
     226 2276.63   230.5 2275.18  234.532272.304   236.2 2271.25   241.4 2271.21
   253.3 2272.32   256.7 2273.75   268.1 2281.66   284.6 2295.31   297.8 2303.01
   332.5 2317.82   362.2 2332.15   417.4 2354.45   502.5  2392.6   570.6  2425.6
   587.5 2432.85   634.2 2458.51   708.2  2493.8   731.9 2503.72   769.6 2517.58
#Mann= 5 ,-1,0
       0      .1       0      90     .06       0  234.53    .045       0
   253.3     .06       0  257.02      .1       0
#XS Ineff= 2 , 0
           205.1 2282.28
Permanent Ineff=
       F       F
Bank Sta=234.53,253.3
XS Rating Curve= 0 ,0
Exp/Cntr(USF)=0,0
Exp/Cntr=0.3,0.1

Type RM Length L Ch R = 1 ,7040    ,177.9,178.2,178.5
XS GIS Cut Line= 3
 2210771.7477199407293.3536914682210519.93201869407585.997955417
2210227.64541357407743.675146608
#Sta/Elev= 30
       0 2331.85    36.4 2314.06    73.6 2297.89   103.6 2290.25   121.1 2284.32
     137  2275.3   152.7 2268.63   158.4 2267.25   163.4 2267.25   175.4 2271.45
     195 2271.45     201 2270.46   215.1 2265.94   220.8 2265.29227.18742265.918
   237.8 2269.01     252 2269.66   257.7 2271.81   263.4 2275.31   277.5 2289.86
     290 2298.59   334.3 2321.53   369.2 2340.94   385.3 2351.13     454 2390.67
   463.1 2397.14   494.5 2415.14     563 2450.28   637.1 2481.37   718.2 2509.25
#Mann= 5 ,-1,0
       0      .1       0     140     .06       0   215.1    .045       0
227.1874     .06       0     270      .1       0
#XS Ineff= 2 , 0
          181.18 2282.19
Permanent Ineff=
       F       F
Bank Sta=215.1,227.1874
XS Rating Curve= 0 ,0
Exp/Cntr=0.3,0.1

Type RM Length L Ch R = 1 ,6862    ,154.4,164.5,175.9
XS GIS Cut Line= 5
2210764.43751565407268.4555910942210566.44699158407286.206465665
2210513.19436787407323.0736666982210459.94174416407383.153549861
2210098.09699328407510.140575639
#Sta/Elev= 30
       0 2334.87    16.3 2325.51    28.4 2320.29    52.5 2315.24    64.5  2311.8
   108.7 2296.62   156.9 2283.92     193 2278.54   198.8 2275.95   216.9 2264.14
   225.9 2263.33   245.3 2265.75   260.2 2266.21   289.2 2264.88   299.8 2261.62
   302.6 2261.31   314.5 2261.76   325.2 2264.02   331.4 2266.24   337.5 2269.88
   351.5 2280.47   360.5 2285.66     386 2296.89   415.7 2305.61   453.8 2324.49
     507 2345.05   542.9 2360.28   606.4 2383.75   652.8 2402.47   727.3  2435.3
#Mann= 5 ,-1,0
       0      .1       0      90     .06       0     190      .1       0
   299.8    .045       0   314.5      .1       0
#XS Ineff= 1 ,-1
   208.6  259.54 2266.43
Permanent Ineff=
       F
Bank Sta=299.8,314.5
XS Rating Curve= 0 ,0
Exp/Cntr(USF)=0,0
Exp/Cntr=0.3,0.1

Type RM Length L Ch R = 1 ,6697    ,205,207.4,209.2
XS GIS Cut Line= 4
2210814.56814482407256.5059689482210503.02591892407219.160213162
2210404.74761422407201.4701183162210047.01458511407205.401250504
#Sta/Elev= 30
       0 2365.53    30.6 2352.34    54.8 2337.52    70.9 2329.22    99.1 2317.68
   111.2 2314.47   143.4 2308.27   175.6 2297.06   183.7    2295   195.8 2289.81
     220 2281.84   280.4 2276.69   288.4 2273.34   304.6 2263.06   328.3 2262.14
   339.6  2258.3   352.4 2256.15   357.3 2255.82   362.7 2256.07   407.5 2261.48
   418.2 2263.92   425.8 2267.62   438.8 2276.41   470.2 2303.88   502.2 2326.47
   538.2 2348.18   673.4 2424.61   725.9 2458.18   762.1 2479.03   771.4 2485.61
#Mann= 5 ,-1,0
       0      .1       0     140     .06       0     240      .1       0
   352.4    .045       0   362.7      .1       0
Bank Sta=352.4,362.7
XS Rating Curve= 0 ,0
Exp/Cntr(USF)=0,0
Exp/Cntr=0.3,0.1

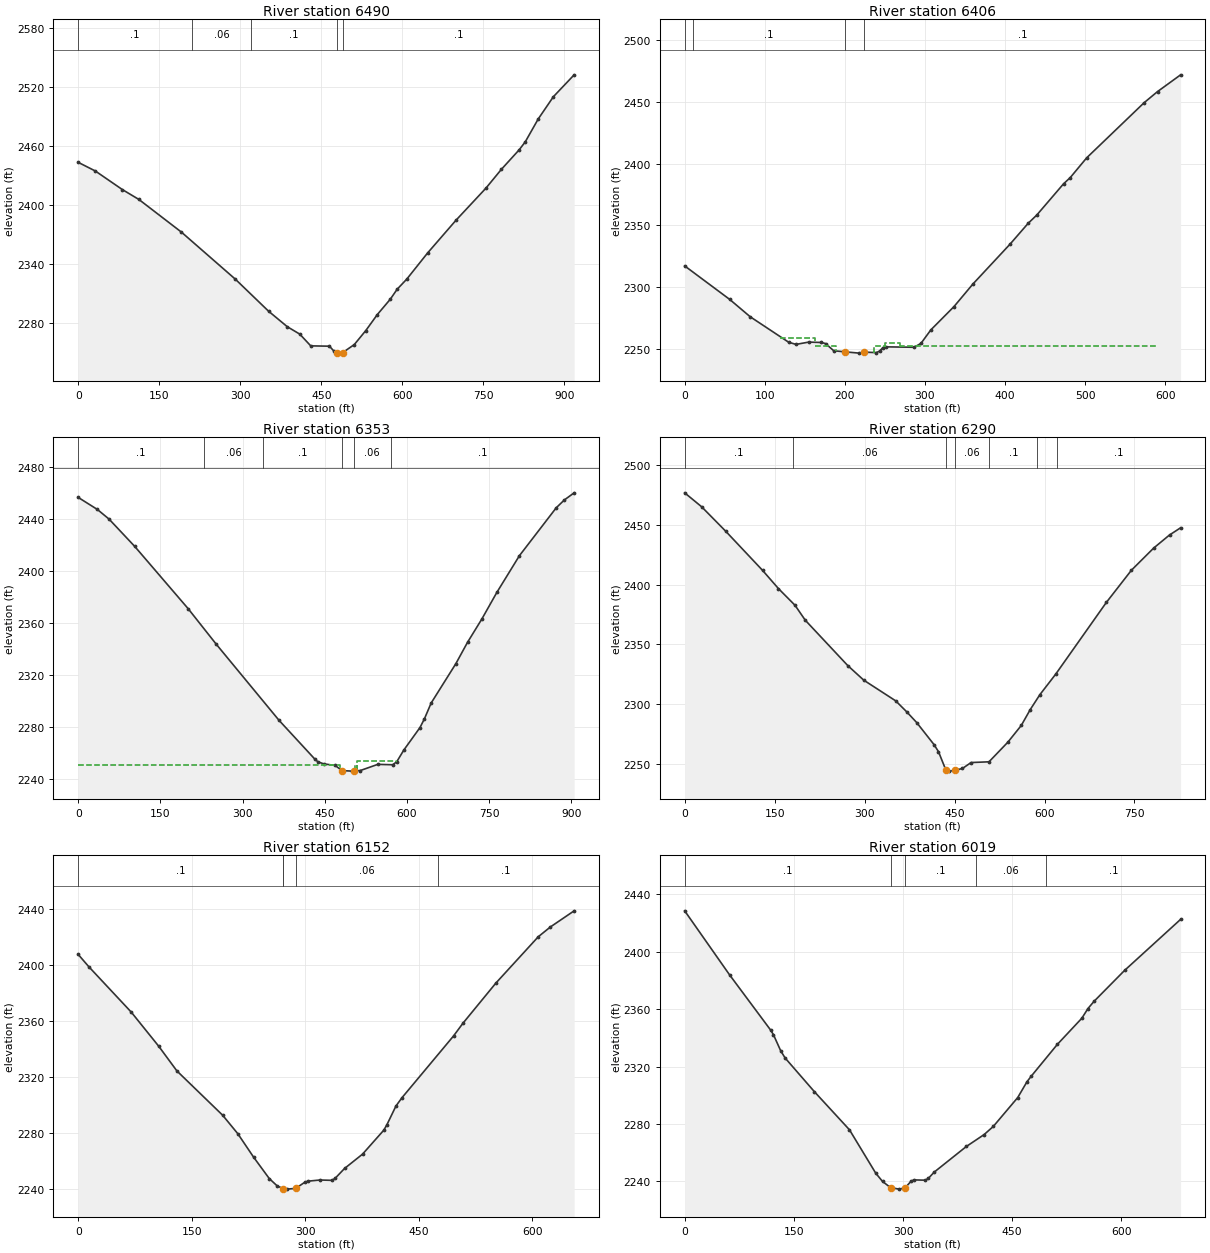
Type RM Length L Ch R = 1 ,6490    ,60.5,83.5,106.3
BEGIN DESCRIPTION:
structure xs 4
END DESCRIPTION:
XS GIS Cut Line= 4
2210962.99453873407205.8784951282210655.03357098407070.980645294
2210368.68475969406951.1317786762210097.80722763406934.219954636
#Sta/Elev= 30
       0 2443.39    31.7 2434.56    81.6 2415.66   112.3 2405.55   190.9 2372.29
   290.9  2324.2   352.3  2291.6     387 2275.74   410.1 2268.19   430.4 2256.21
   465.1 2255.88   473.7 2250.62   478.1 2249.39   485.9  2248.8   489.6 2249.38
     511 2257.51   532.4 2271.86   553.7 2288.15   577.8 2303.88   590.4 2313.98
   608.2 2324.31   646.6 2350.87   699.2 2384.29   754.6 2417.01   783.4 2436.32
   816.1 2456.09   827.5 2464.29   851.5 2487.64   879.6 2510.36     918 2532.66
#Mann= 5 ,-1,0
       0      .1       0     210     .06       0     320      .1       0
   478.1    .045       0   489.6      .1       0
Bank Sta=478.1,489.6
XS Rating Curve= 0 ,0
Exp/Cntr=0.5,0.3

Type RM Length L Ch R = 1 ,6406    ,62.2,53.4,57.6
BEGIN DESCRIPTION:
structure xs 3; 11.9  ft between structure and xs
END DESCRIPTION:
XS GIS Cut Line= 5
2210685.53914406407079.2151123612210545.78397884406958.814770695
2210567.45255639406862.1991808182210439.00632587406830.983556141
2210244.66188527406770.143387149
#Sta/Elev= 30
       0 2317.25    56.3 2290.08    81.8 2276.09     130  2255.4   139.1 2253.72
   154.9 2255.57   170.8 2255.26     176 2254.37   186.1 2248.57200.8142 2247.64
     218 2246.64223.99452247.475   239.4 2247.04   243.5 2248.36   247.6 2251.17
   251.7 2251.72   286.6 2251.39   295.1 2254.57   307.4 2265.45   336.3 2284.31
   359.9 2302.56   406.3 2334.85   428.9  2351.7   439.6 2358.35   473.1 2383.69
   481.5 2388.75     502 2404.73   573.7 2449.34   590.5 2458.37   619.3 2471.92
#Mann= 4 ,-1,0
       0     .06       0      10      .1       0200.8142    .045       0
223.9945      .1       0
#XS Ineff= 6 ,-1
       0  119.55 2252.28  119.55  163.36 2258.67  163.36   189.2 2252.28
   236.4  250.05 2252.22  250.05  268.98 2254.52  268.98   590.4 2252.22
Permanent Ineff=
       F       F       F       F       F       F
Bank Sta=200.8142,223.9945
XS Rating Curve= 0 ,0
Exp/Cntr(USF)=0,0
Exp/Cntr=0.5,0.3

Type RM Length L Ch R = 1 ,6353    ,75.9,62.6,32
BEGIN DESCRIPTION:
structure xs 2; 8.2 ft between structure & xs
END DESCRIPTION:
XS GIS Cut Line= 6
2210985.01291081407150.2154588742210696.89417417407044.648618613
2210591.41363944406948.8009944582210604.73639077406858.891475858
2210444.88019293406816.4405544942210259.35070185406742.592128545
#Sta/Elev= 30
       0 2456.67      35 2447.41    56.3 2440.02   103.1 2419.06   200.7  2371.2
   252.2 2343.78   366.4 2285.52   432.1 2255.55   437.5 2253.57   448.3 2251.97
   469.2 2250.75   481.4 2246.81   500.2  2246.4502.84682246.714   514.5 2246.79
   546.9  2251.6     574 2251.29   581.4 2253.55   594.4 2262.62   623.9 2279.89
   631.9  2286.5   644.3 2298.74   689.3 2328.91   710.7 2345.38   736.6 2363.11
   764.1 2383.64   805.4 2411.92   872.7 2448.76   887.5 2454.75   905.3  2460.2
#Mann= 6 ,-1,0
       0      .1       0     230     .06       0  336.85      .1       0
   481.4    .045       0502.8468     .06       0  570.26      .1       0
#XS Ineff= 3 ,-1
       0   478.4    2251   504.7     508    2251     508  579.71  2254.2
Permanent Ineff=
       F       F       F
Bank Sta=481.4,502.8468
XS Rating Curve= 0 ,0
Exp/Cntr(USF)=0,0
Exp/Cntr=0.5,0.3

Type RM Length L Ch R = 1 ,6290    ,142.7,138,134.8
BEGIN DESCRIPTION:
structure xs 1
END DESCRIPTION:
XS GIS Cut Line= 4
2211033.69652804407056.9175455612210737.73151171406915.705478948
2210483.03394864406791.2583152212210278.63109423406722.909095765
#Sta/Elev= 30
       0 2476.94    28.3 2465.24    68.2 2444.88     130  2411.9   156.3 2396.73
     184 2382.71   201.1 2370.19     272 2332.16   298.6 2319.98   351.9 2302.63
   369.9 2293.62   386.8 2284.49   415.7 2266.02   423.2 2260.07   435.7  2244.4
     441 2243.77   450.6 2244.43   463.2 2246.02   477.5 2250.96   507.4 2251.58
   538.9 2268.05   561.2 2282.02   576.2 2295.36   592.3 2307.87   618.5 2324.94
     703 2385.07   744.9 2412.11   781.9 2430.62   808.4 2441.62   826.9 2447.65
#Mann= 7 ,-1,0
       0      .1       0     180     .06       0   435.7    .045       0
   450.6     .06       0  507.93      .1       0  587.93     .06       0
   621.4      .1       0
Bank Sta=435.7,450.6
XS Rating Curve= 0 ,0
Exp/Cntr(USF)=0,0
Exp/Cntr=0.3,0.1

Type RM Length L Ch R = 1 ,6152    ,133.5,132.9,133.3
XS GIS Cut Line= 3
2210945.89965676406761.9526298772210562.90775333406722.081647975
2210292.81678129 406712.50035548
#Sta/Elev= 30
       0 2407.37    13.8 2398.73    70.1 2366.16   106.3 2341.85   130.4 2324.15
   190.8 2292.52   210.9 2279.27   231.7 2262.57   252.4 2247.28   263.1  2241.9
   271.2 2240.04   275.5 2239.69   287.3 2240.19   299.3 2244.57   303.4 2245.36
   319.4 2246.21   335.5 2245.96   339.5 2247.42   351.9 2254.44   375.7 2264.69
   403.8 2281.83   407.9  2285.7   419.8 2299.04   427.8 2305.01   495.9 2349.11
   508.4 2358.25   551.9 2386.93   607.9 2420.02   623.9 2427.01   655.3 2438.54
#Mann= 5 ,-1,0
       0      .1       0     270     .06       0   271.2    .045       0
   287.3     .06       0  475.06      .1       0
Bank Sta=271.2,287.3
XS Rating Curve= 0 ,0
Exp/Cntr(USF)=0,0
Exp/Cntr=0.3,0.1

Type RM Length L Ch R = 1 ,6019    ,203.7,195.8,186.5
XS GIS Cut Line= 3
2210969.59188953406627.2793503322210564.77751629406590.162947579
2210302.76189671406673.032972436
#Sta/Elev= 30
       0 2428.51    61.7 2383.88   117.9 2345.55   121.9 2342.26     132 2330.91
     138 2325.97   178.2  2302.5   226.4 2275.94   262.5  2245.7   271.8 2239.97
   282.9 2235.63   294.6 2234.61   302.7 2235.48   310.7 2239.95   314.7 2241.04
   330.8 2240.84   334.8 2242.13   342.8 2246.47     387 2264.34   411.3  2272.6
   423.9 2278.25   457.5 2298.39   470.3 2309.47   476.4 2313.49     512 2335.48
   545.6 2353.68     554 2360.42   562.3 2365.42   604.3 2386.98   681.3 2422.57
#Mann= 5 ,-1,0
       0      .1       0   282.9    .045       0   302.7      .1       0
     400     .06       0  496.51      .1       0
Bank Sta=282.9,302.7
XS Rating Curve= 0 ,0
Exp/Cntr(USF)=0,0
Exp/Cntr=0.3,0.1

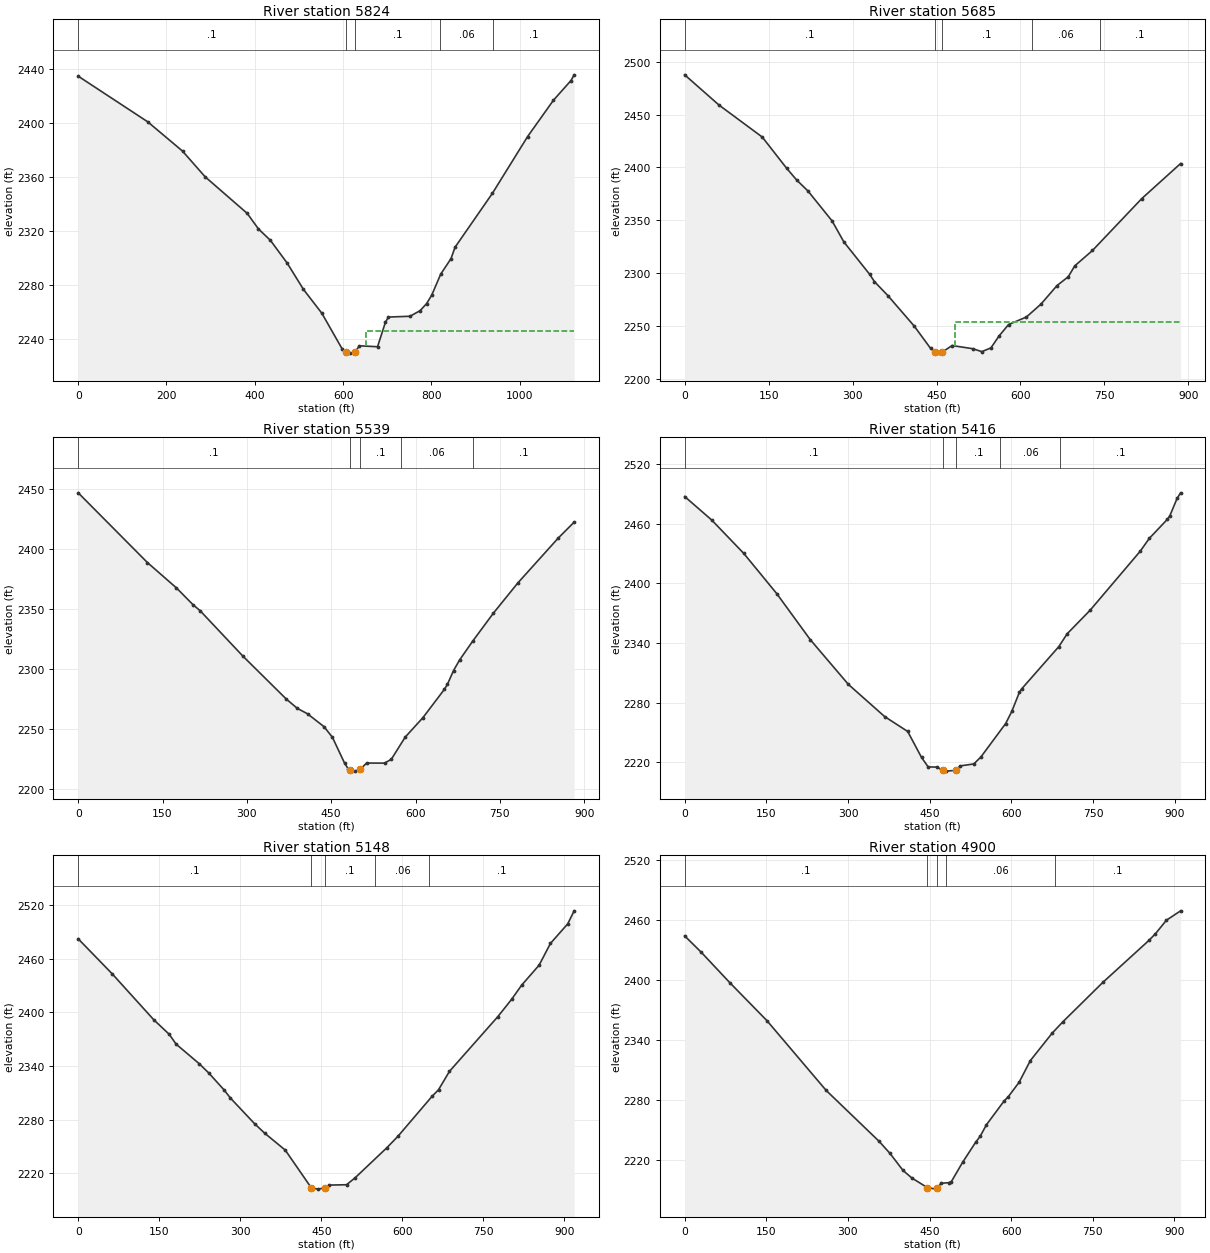
Type RM Length L Ch R = 1 ,5824    ,147.5,139.1,129.2
XS GIS Cut Line= 2
2211191.75641446406096.3753541332210223.78449028406666.645698809
#Sta/Elev= 30
       0    2435   157.4  2401.2   236.3  2379.5   287.4 2360.49     383 2333.31
   408.1 2321.92   435.6  2313.3   473.6 2296.43   510.2 2277.05     552 2259.33
   598.4 2232.67  605.84 2230.46   616.7 2229.82   626.3 2230.45   637.2 2235.25
   678.1 2234.56   695.9 2252.66   702.9 2256.55   751.6 2257.13   774.5 2261.29
   789.1 2266.46   800.8 2272.74   821.2 2288.34   844.5 2299.82   853.7 2308.29
   938.1 2348.12  1018.1 2390.28  1076.6 2417.19  1116.3 2431.76  1123.5    2436
#Mann= 5 ,-1,0
       0      .1       0  605.84    .045       0   626.3      .1       0
     820     .06       0     940      .1       0
#XS Ineff= 2 , 0
                          650.98         2246.58
Permanent Ineff=
       F       F
Bank Sta=605.84,626.3
XS Rating Curve= 0 ,0
Exp/Cntr(USF)=0,0
Exp/Cntr=0.3,0.1

Type RM Length L Ch R = 1 ,5685    ,148.5,145.6,141.6
XS GIS Cut Line= 4
2210690.83173107405898.6036705562210541.11281996 406361.37121399
2210526.59462252406434.869588535 2210258.9153572406619.069218568
#Sta/Elev= 30
       0 2487.53    61.3 2458.97   138.6 2428.72     182 2399.35   200.3 2387.98
   220.2 2377.81   263.4 2349.44   284.4 2329.61   330.6 2298.91     339 2292.11
   363.1 2278.83   410.1 2250.07   439.3 2229.02   447.3 2225.43   455.2 2224.46
   459.8 2225.25   477.8 2231.64   514.7 2228.64     531 2225.87   547.3 2229.43
   561.7 2240.65   578.8 2251.49   610.7 2258.61   636.6 2270.77   665.4 2288.35
   685.5 2296.68     697 2306.93   728.7 2321.49   816.7  2370.5   886.2 2403.71
#Mann= 5 ,-1,0
       0      .1       0   447.3    .045       0   459.8      .1       0
   621.3     .06       0   741.3      .1       0
#XS Ineff= 2 , 0
                          483.87         2254.14
Permanent Ineff=
       F       F
Bank Sta=447.3,459.8
XS Rating Curve= 0 ,0
Exp/Cntr(USF)=0,0
Exp/Cntr=0.3,0.1

Type RM Length L Ch R = 1 ,5539    ,119,122.9,128.6
XS GIS Cut Line= 4
 2210550.0615689405863.4055961982210406.68912044406294.888393465
2210409.42002422406421.875419242 2210205.9676926406643.078625436
#Sta/Elev= 30
       0 2446.57   123.1 2388.57   174.7 2367.49   204.2 2353.51   216.8 2348.54
   292.7 2310.85   369.9 2275.12   389.7 2267.29   407.9 2262.75   437.3 2252.02
   452.2  2243.2     474 2221.54     480 2217.18   482.72216.354     493 2215.06
   501.5 2216.48     513 2221.78     545 2221.73     557 2224.93   581.7 2243.37
   613.2 2259.56   651.4 2283.11   656.8 2287.29   667.7 2298.75   678.3 2307.44
   701.7 2323.18   738.4 2346.39   781.8 2371.48   853.8 2408.89   882.2 2422.19
#Mann= 5 ,-1,0
       0      .1       0   482.7    .045       0   501.5      .1       0
  574.68     .06       0   701.7      .1       0
Bank Sta=482.7,501.5
XS Rating Curve= 0 ,0
Exp/Cntr(USF)=0,0
Exp/Cntr=0.3,0.1

Type RM Length L Ch R = 1 ,5416    ,271.3,267.7,266.6
XS GIS Cut Line= 2
2210428.27171587405857.8787923262210159.32764653406728.200051919
#Sta/Elev= 30
       0 2487.31    49.5 2463.75   108.3 2430.26     169 2389.74   230.6 2343.44
   300.7 2298.38   367.3 2266.04   409.6 2251.08     435 2224.99   447.2 2215.44
   463.3 2215.22   474.5 2211.91   480.7 2211.18   498.5 2212.05   505.8 2216.43
     531 2218.39   544.1 2225.43   589.6 2259.07   600.8 2271.21   614.7 2290.38
   618.9 2293.87   687.2 2336.39   702.6 2349.35   744.5 2372.86   836.6 2432.25
   853.3 2445.17   886.8 2464.52     891 2467.83   904.6 2485.65   910.9 2491.03
#Mann= 5 ,-1,0
       0      .1       0   474.5    .045       0   498.5      .1       0
     580     .06       0     690      .1       0
Bank Sta=474.5,498.5
XS Rating Curve= 0 ,0
Exp/Cntr=0.3,0.1

Type RM Length L Ch R = 1 ,5148    ,249.2,248.7,248
XS GIS Cut Line= 2
2210117.36631345405771.0244730732209969.51831345406676.925473073
#Sta/Elev= 30
       0 2482.42      63 2443.19     140 2391.72   168.4  2375.6   181.2 2364.57
     224 2342.64   241.3 2332.47   269.7 2313.51   281.8 2304.16   326.4 2275.54
     345 2264.97   383.2 2245.94   431.5 2203.68     444 2202.27   456.4 2203.71
   464.2 2206.79   496.6 2207.18   512.9 2215.17   570.9  2248.4   591.8 2261.43
   654.7 2306.01   666.9 2313.54   687.1 2334.09   776.3 2395.09   802.1 2414.66
   820.9  2430.7   853.1 2452.99     874 2477.28     906 2499.19   917.9 2513.77
#Mann= 5 ,-1,0
       0      .1       0   431.5    .045       0   456.4      .1       0
     550     .06       0     650      .1       0
Bank Sta=431.5,456.4
XS Rating Curve= 0 ,0
Exp/Cntr=0.3,0.1

Type RM Length L Ch R = 1 ,4900    ,253.9,251.1,247
XS GIS Cut Line= 2
2209857.77746063  405739.14947422209741.71404997406643.078625436
#Sta/Elev= 30
       0  2444.3    30.3 2427.99    82.7 2397.55   151.3 2359.29   260.1 2289.41
   357.1 2238.57   377.1 2226.49   401.3 2209.26   417.4 2201.76   445.7 2192.18
   461.8 2190.59   464.3 2191.86   471.4  2196.5     486 2197.08     490 2198.11
   510.7 2217.45   534.4 2237.32   542.9 2243.45   554.5 2255.08   586.8 2278.79
   594.9 2283.37   614.4 2297.53   635.2 2319.39   675.1 2346.74   694.5    2358
   768.3 2397.66     853 2439.73   865.1 2446.48   885.2    2460   911.3  2469.4
#Mann= 5 ,-1,0
       0      .1       0   445.7    .045       0   464.3      .1       0
     480     .06       0     680      .1       0
Bank Sta=445.7,464.3
XS Rating Curve= 0 ,0
Exp/Cntr(USF)=0,0
Exp/Cntr=0.3,0.1