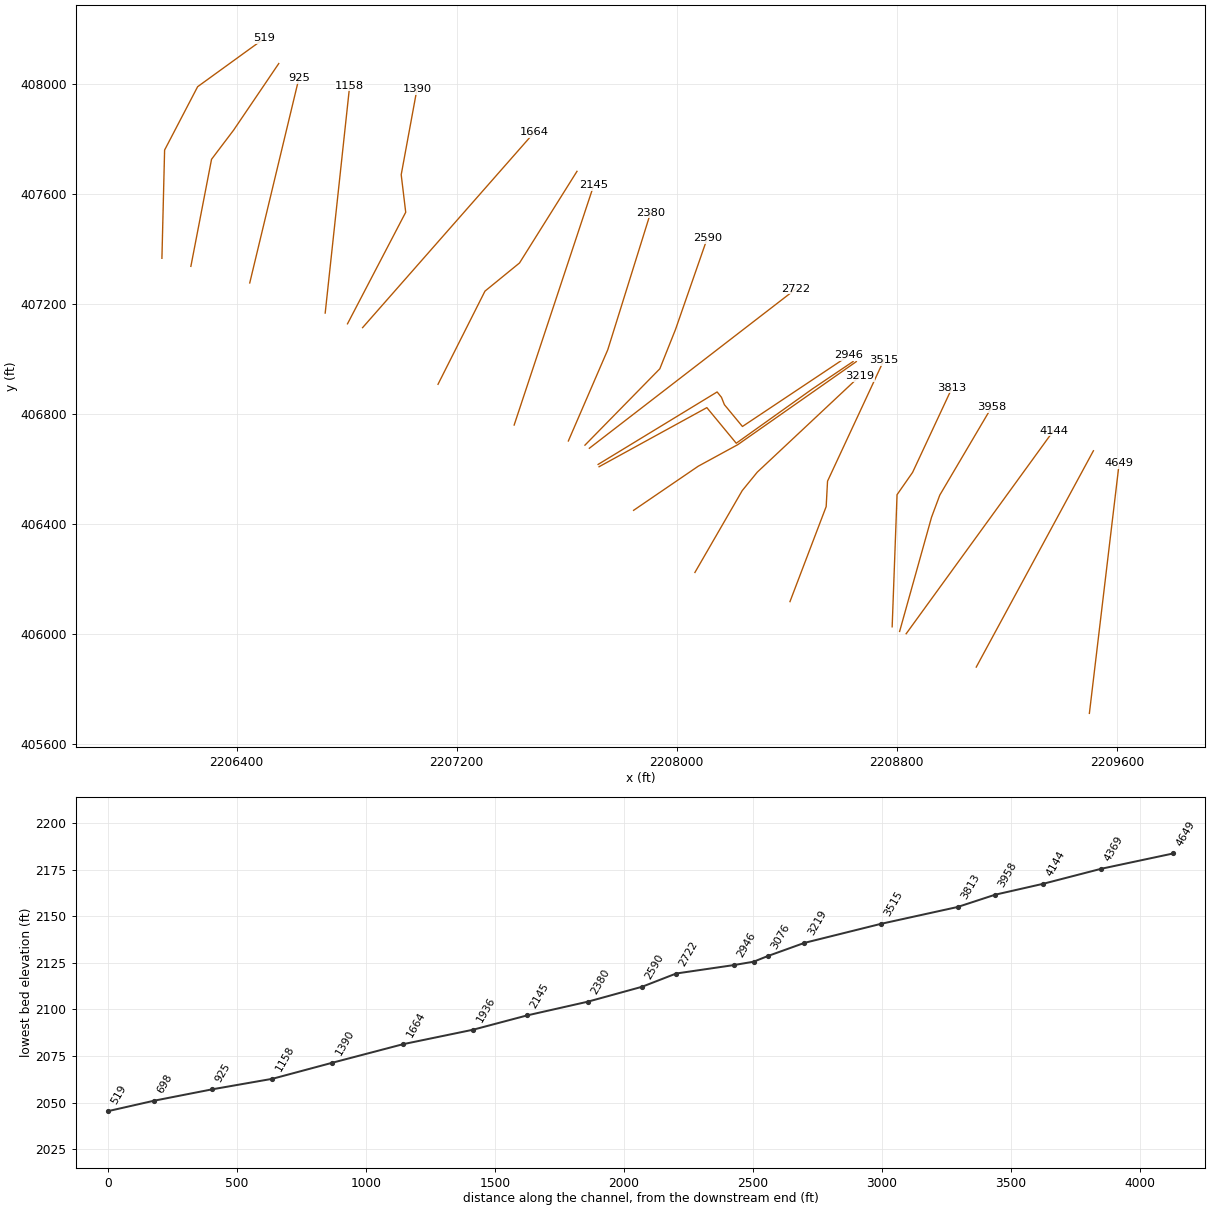
HEC-RAS study ISLNDLCKRN.prj: ISLNDLCKRN

--- ISLNDLCKRN.g01 (geometry) --- (continued)

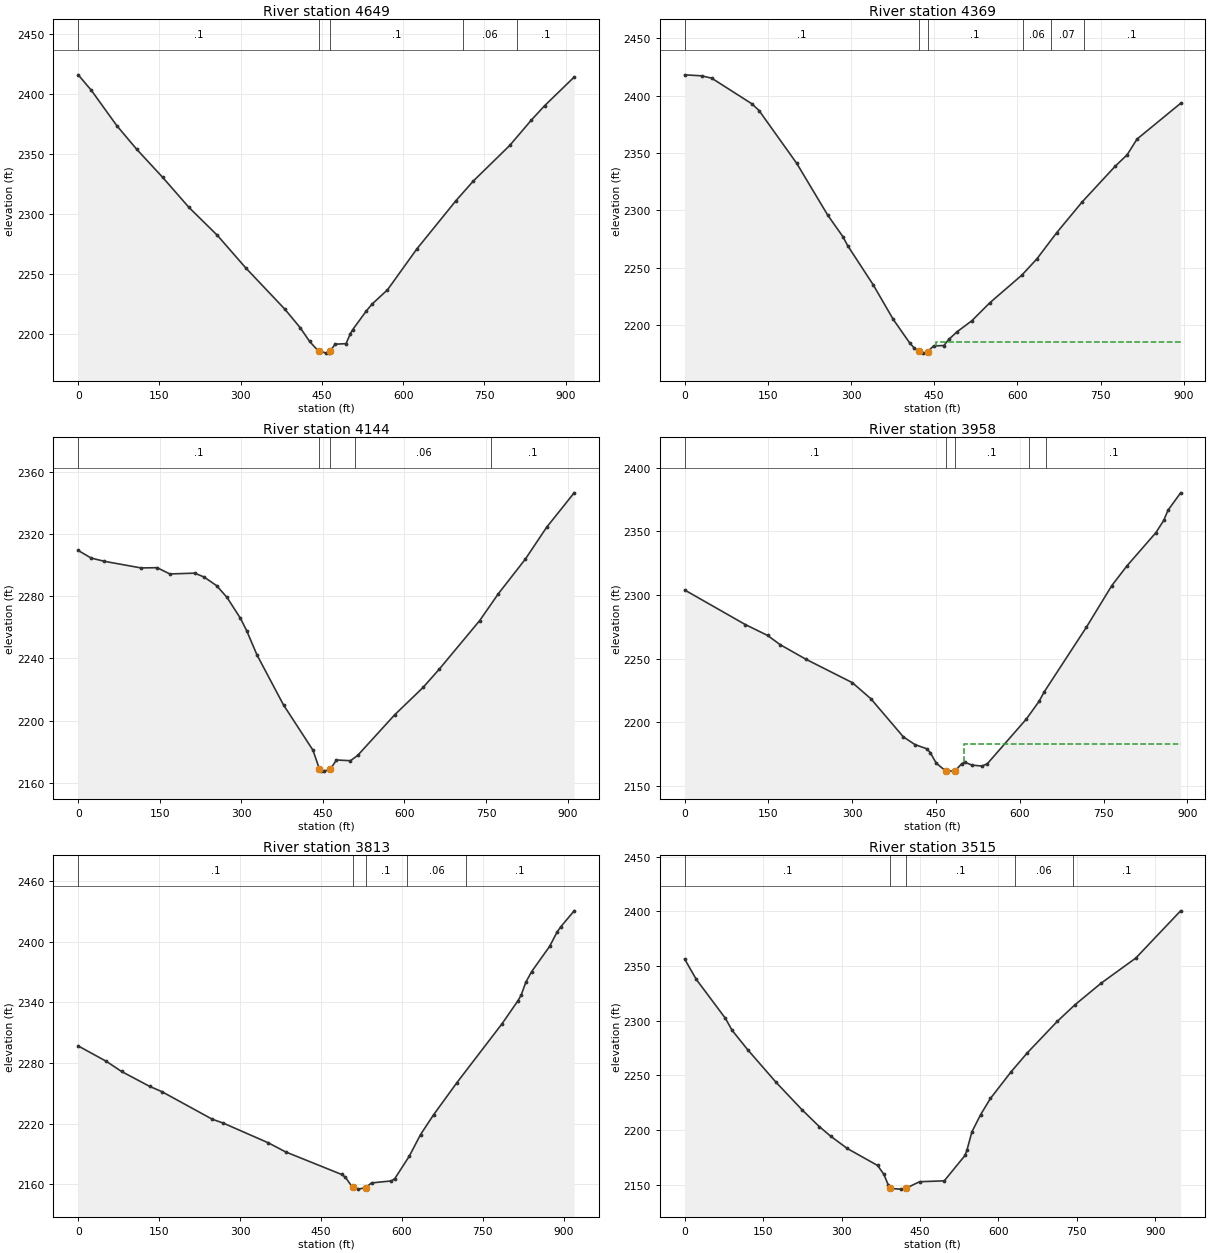
Type RM Length L Ch R = 1 ,4649    ,284.6,280,274.8
XS GIS Cut Line= 2
     2209500.377      405710.203     2209608.642        406619.4
#Sta/Elev= 30
       0 2416.26    24.1  2403.4    71.5 2373.66   107.7 2354.23   156.1 2330.55
   204.4 2305.55   256.8 2282.25   309.1 2255.11   381.7 2220.42   409.9 2205.01
   427.3 2193.54   442.1 2186.23   445.3 2185.56   458.2 2183.82   462.2 2184.17
465.27472185.707   474.3 2191.28   494.4 2191.74   502.5  2200.1   506.5 2203.29
   531.6 2218.86   542.4 2224.75     571  2236.7   625.2 2270.85   697.2 2311.06
   729.6 2327.64   796.6 2357.25   836.8 2378.59     861 2390.43   915.6 2414.39
#Mann= 5 ,-1,0
       0      .1       0   445.3    .045       0465.2747      .1       0
     710     .06       0     810      .1       0
Bank Sta=445.3,465.2747
XS Rating Curve= 0 ,0
Exp/Cntr=0.3,0.1

Type RM Length L Ch R = 1 ,4369    ,225.5,224.4,221.8
XS GIS Cut Line= 2
2209089.02804651405878.4255669892209515.04903622406664.925855677
#Sta/Elev= 30
       0 2418.17    30.4  2417.3    48.6 2415.29   121.4 2392.86   134.2 2387.01
   202.1    2341   258.1 2295.78   285.2 2277.22   294.3 2269.01   339.8 2235.31
   376.1 2205.05     406 2184.32   414.5 2179.76   422.82177.043   430.7 2175.56
   438.1 2176.79   448.9 2181.81   467.6  2182.2   476.2 2187.46   491.2 2194.14
   517.8 2203.74   550.2 2219.38   608.2  2243.6   635.5 2257.87   671.2 2280.68
   717.3 2307.58   776.5 2338.49   798.1 2348.48   815.8 2362.11   894.5 2393.34
#Mann= 6 ,-1,0
       0      .1       0   422.8    .045       0   438.1      .1       0
     610     .06       0     660     .07       0     720      .1       0
#XS Ineff= 2 , 0
                          453.38         2184.85
Permanent Ineff=
       F       F
Bank Sta=422.8,438.1
XS Rating Curve= 0 ,0
Exp/Cntr(USF)=0,0
Exp/Cntr=0.3,0.1

Type RM Length L Ch R = 1 ,4144    ,184.3,186.5,191.2
XS GIS Cut Line= 2
2208834.28378845405999.6646846182209370.00578845406737.954684618
#Sta/Elev= 30
       0 2309.31    23.7 2304.44    48.3 2302.33   115.5 2298.08   145.2 2298.24
   168.5 2294.21   214.4 2294.73   231.6 2292.21   254.5 2286.72   273.7 2279.14
   298.4  2265.7   309.7 2257.87   328.9 2242.13   377.6 2210.05   431.8 2180.96
   443.5 2169.01   445.9 2167.75   451.6 2167.51   463.5 2168.64     475 2174.68
   500.8  2174.2     514 2177.61   582.1  2203.7   634.5 2221.34     664    2233
   738.5 2264.28   772.8 2281.53   822.3 2303.69   861.6  2324.2   912.2 2346.34
#Mann= 5 ,-1,0
       0      .1       0   443.5    .045       0   463.5      .1       0
     510     .06       0     760      .1       0
Bank Sta=443.5,463.5
XS Rating Curve= 0 ,0
Exp/Cntr=0.3,0.1

Type RM Length L Ch R = 1 ,3958    ,147.1,145.1,140.3
XS GIS Cut Line= 4
2208810.47586093406008.1434965472208926.53927159406423.240871132
2208956.57921317406503.802532647  2209145.011574406823.318274927
#Sta/Elev= 30
       0 2303.95   108.6 2276.79   148.3 2268.28     171 2260.99   217.1 2249.53
   300.1 2231.16   333.3 2218.53   391.5 2188.54   412.3 2182.47   433.8 2179.15
     440 2175.97   450.2 2168.01   467.2 2161.78     480 2161.63   484.3 2161.93
     496  2167.5   501.4 2168.58   514.6 2166.34   532.3 2165.62   541.8 2167.42
   611.5 2202.46   634.6 2216.53   643.3 2223.64   719.3 2274.78   764.7 2307.41
   791.8  2322.9   843.7 2349.05   857.6 2358.59   865.3  2366.6   887.9  2380.3
#Mann= 5 ,-1,0
       0      .1       0   467.2    .045       0   484.3      .1       0
     617     .06       0     647      .1       0
#XS Ineff= 2 , 0
                          500.77         2183.15
Permanent Ineff=
       F       F
Bank Sta=467.2,484.3
XS Rating Curve= 0 ,0
Exp/Cntr(USF)=0,0
Exp/Cntr=0.3,0.1

Type RM Length L Ch R = 1 ,3813    ,289,297.2,304.8
XS GIS Cut Line= 4
2208783.38650986406024.9565933182208801.14811207 406505.23923396
2208857.67782032406586.3470762312209001.44670162 406894.36356445
#Sta/Elev= 30
       0 2296.81    52.3 2281.52    80.3 2271.54   132.3 2256.81   155.4 2251.47
   248.4 2224.27   268.4 2220.53   352.5 2200.86   384.5  2191.9   488.5 2169.53
   495.2  2166.9   508.6 2156.73   519.5 2155.04   532.6  2156.5   543.9 2161.21
   580.5 2163.17     587 2165.51   613.6 2187.55   634.6    2209   658.7 2228.57
   701.8 2260.29   785.7 2318.78   815.2 2341.55     821 2346.97   829.8 2359.88
   840.7 2370.49   873.9 2395.36   887.4 2409.22   894.7 2414.87   919.4 2430.57
#Mann= 5 ,-1,0
       0      .1       0   508.6    .045       0   532.6      .1       0
  609.47     .06       0  719.47      .1       0
Bank Sta=508.6,532.6
XS Rating Curve= 0 ,0
Exp/Cntr(USF)=0,0
Exp/Cntr=0.3,0.1

Type RM Length L Ch R = 1 ,3515    ,306.8,296.6,286.3
XS GIS Cut Line= 4
2208411.84480802406116.4370654582208543.48373149406461.983721333
2208548.45066368406554.3917636772208753.49048302406994.921617461
#Sta/Elev= 30
       0 2356.27    22.2 2337.76    77.8 2302.17    90.7 2291.17   120.6 2273.37
   174.4 2243.81     224 2218.72   257.6 2203.07     279 2194.44   310.8 2183.15
   368.9  2167.6     381 2159.39     389 2150.01     393 2146.57     413 2145.98
   422.9 2146.75   449.1 2152.75   496.3 2153.56     536  2176.8   539.5 2181.33
   549.2 2198.42   565.9 2214.15   584.6  2228.9   624.2 2253.31   655.1 2270.61
   712.5 2299.42     746 2314.44   796.3  2334.3   862.5 2357.24   948.2 2400.42
#Mann= 5 ,-1,0
       0      .1       0     393    .045       0   422.9      .1       0
  632.31     .06       0  742.31      .1       0
Bank Sta=393,422.9
XS Rating Curve= 0 ,0
Exp/Cntr(USF)=0,0
Exp/Cntr=0.3,0.1

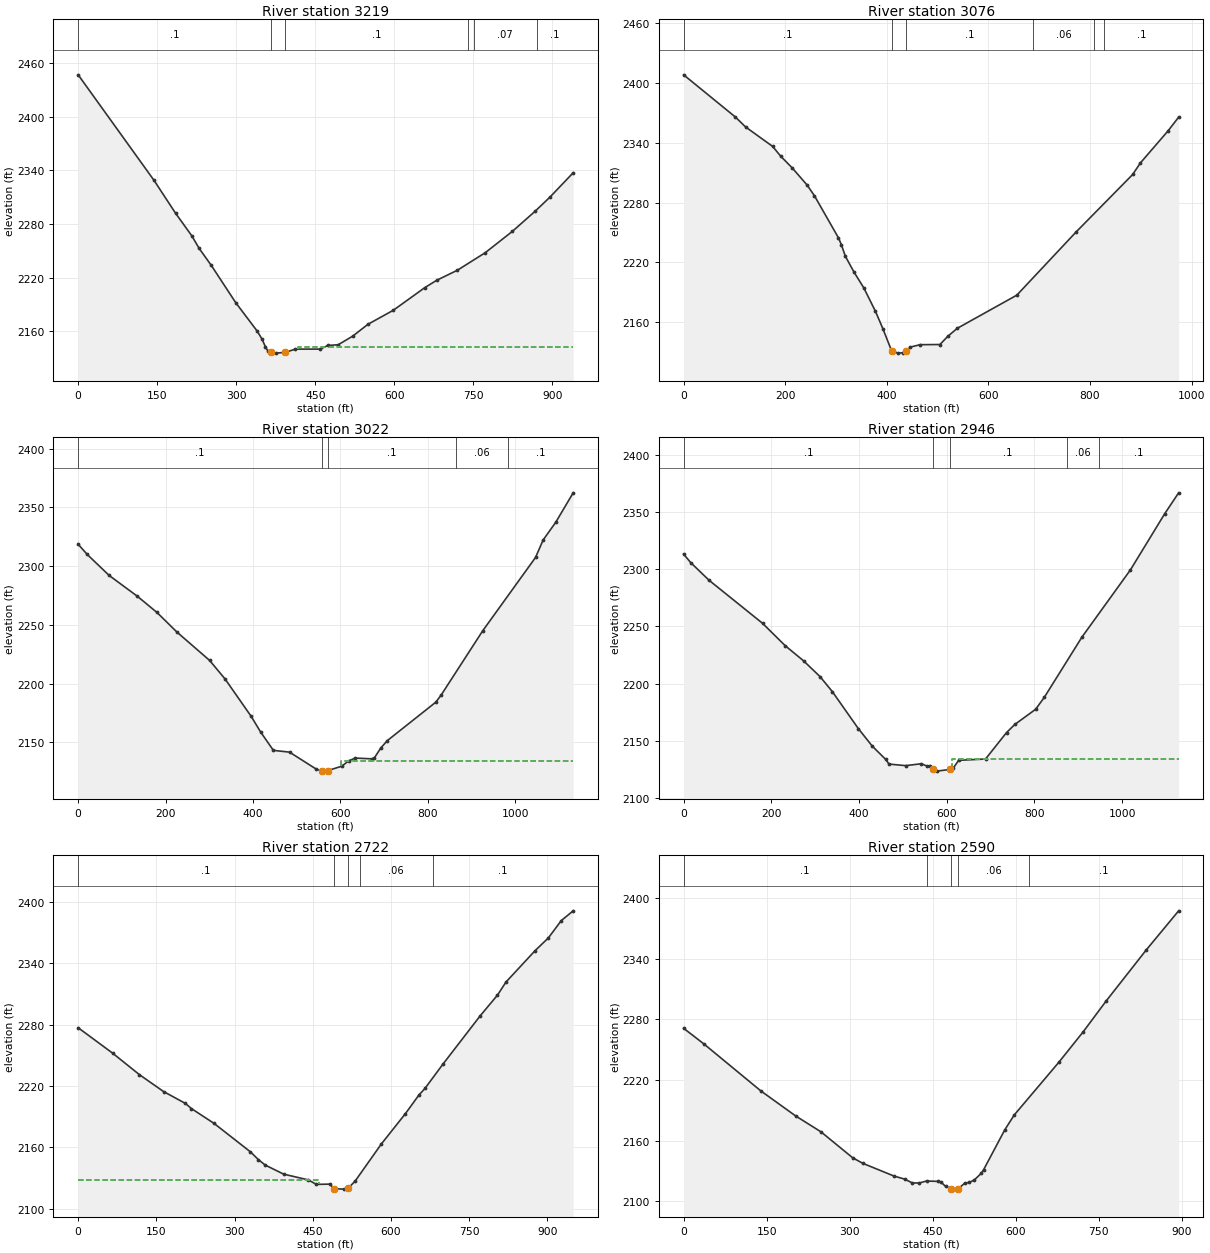
Type RM Length L Ch R = 1 ,3219    ,149.4,142.9,135.6
XS GIS Cut Line= 4
2208066.30458084 406222.519443292208238.35151899406520.187955328
2208292.96959459406587.095097942 2208664.3725087406935.285329914
#Sta/Elev= 30
       0 2446.69   143.9 2328.81   184.8 2292.08   215.6 2266.83   229.5 2252.84
   252.6 2233.78     299 2192.12   339.5 2160.51   348.7 2151.63   355.4 2142.71
     360 2138.17   365.7 2136.64   365.7 2136.63   376.1 2135.75   393.42136.692
   412.2 2140.23   459.4 2140.23   473.5 2144.32   493.4 2145.12     521 2154.75
   549.9 2167.98   598.1 2183.68   657.5 2208.83   680.1 2217.06   719.7 2228.41
   772.4 2247.93   823.9 2271.79   866.9 2294.17   895.3  2310.1   939.3 2337.27
#Mann= 6 ,-1,0
       0      .1       0   365.7    .045       0   393.4      .1       0
  740.18     .06       0  750.18     .07       0  870.18      .1       0
#XS Ineff= 2 , 0
                          417.34         2142.39
Permanent Ineff=
       F       F
Bank Sta=365.7,393.4
XS Rating Curve= 0 ,0
Exp/Cntr(USF)=0,0
Exp/Cntr=0.3,0.1

Type RM Length L Ch R = 1 ,3076    ,76.3,53.9,36.9
BEGIN DESCRIPTION:
structure xs 4
END DESCRIPTION:
XS GIS Cut Line= 4
2207843.39377604406448.3738388912208078.51981605406608.836528433
 2208221.9858103406687.0395791162208653.06871383406989.106836084
#Sta/Elev= 30
       0 2408.34   101.9 2365.93     122 2355.94   175.3 2336.37   191.1 2326.54
     214 2314.66   243.1 2297.54   257.6 2286.74   304.8 2244.51   310.5 2237.64
   318.4 2225.94   335.5    2210   354.9 2194.02   377.7 2170.54   392.3 2153.12
   409.6 2130.66   421.8 2128.62   432.3 2129.01   438.2 2130.53     446 2134.65
   465.5  2137.1   504.5 2137.28   520.1 2145.55   538.6 2153.54   655.9 2186.89
   772.4 2250.31   883.9 2308.16   899.2 2319.82   953.7 2352.09   974.4 2365.77
#Mann= 6 ,-1,0
       0      .1       0   409.6    .045       0   438.2      .1       0
  688.06     .06       0  808.06     .07       0  828.06      .1       0
Bank Sta=409.6,438.2
XS Rating Curve= 0 ,0
Exp/Cntr=0.5,0.3

Type RM Length L Ch R = 1 ,3022    ,76.5,76.5,76.5
BEGIN DESCRIPTION:
structure xs 3; 31.6 ft between structure & xs
END DESCRIPTION:
XS GIS Cut Line= 5
2207718.00420768406606.973705239 2208109.7019514406821.715661798
2208216.52766849406692.2865547012208493.27226296406889.673096319
2208641.20641726406989.297220561
#Sta/Elev= 30
       0  2318.6    20.7 2309.94    70.9 2292.08   134.8 2274.56   180.4 2260.58
     226 2243.93   300.8 2219.81   336.2    2204   395.7 2172.33   417.6 2158.88
   446.7  2143.3   483.7 2141.79   544.8 2127.36557.0632  2125.9   563.7 2125.64
     571 2126.08     603  2129.8     619 2134.31   633.7 2136.74     673 2136.08
     678 2136.97   692.3 2145.21   707.4 2151.58   818.5 2184.32   830.3 2190.15
     926 2245.13  1046.7 2307.41    1064 2322.21    1093 2337.36  1132.8 2362.35
#Mann= 5 ,-1,0
       0      .1       0557.0632    .045       0     571      .1       0
  864.52     .06       0  984.45      .1       0
#XS Ineff= 2 , 0
          525.46  2128.4   602.6         2133.99
Permanent Ineff=
       F       F
Bank Sta=557.0632,571
XS Rating Curve= 0 ,0
Exp/Cntr(USF)=0,0
Exp/Cntr=0.5,0.3

Type RM Length L Ch R = 1 ,2946    ,223.4,223.4,223.4
BEGIN DESCRIPTION:
structure xs 2 12.6 ft between structure & opening
END DESCRIPTION:
XS GIS Cut Line= 6
2207714.42748361 406615.267762012208147.02574463406878.737744953
2208162.81410116406859.2421011532208173.42273388406832.508346699
2208239.02133766406753.1849150632208626.49586769407011.417285369
#Sta/Elev= 30
       0 2313.14    16.1 2305.76    58.2 2290.27     180 2252.79   231.5 2233.32
   273.7    2220   311.2 2206.26   339.3 2193.14   398.5 2160.93   430.5 2145.53
     461 2134.01   468.4 2129.98   506.5 2128.62   542.4 2130.28   555.3 2128.18
   561.8 2128.61  568.532125.307   577.2 2123.83   607.3 2125.27   614.9 2126.45
   627.4 2133.24   688.6  2134.4   736.5 2157.49   755.5 2164.57   802.8 2177.77
   822.4 2188.06   908.5 2240.77  1019.2 2299.46  1097.1 2348.28    1129  2366.6
#Mann= 5 ,-1,0
       0      .1       0  568.53    .045       0   607.3      .1       0
   873.3     .06       0  946.35      .1       0
#XS Ineff= 2 , 0
          564.33  2126.4   611.5         2133.99
Permanent Ineff=
       F       F
Bank Sta=568.53,607.3
XS Rating Curve= 0 ,0
Exp/Cntr(USF)=0,0
Exp/Cntr=0.5,0.3

Type RM Length L Ch R = 1 ,2722    ,125.2,132,140
BEGIN DESCRIPTION:
structure xs 1
END DESCRIPTION:
XS GIS Cut Line= 2
2207682.58026206406674.0742131332208434.25685312407253.884933064
#Sta/Elev= 30
       0 2277.02    66.1 2252.17   117.4 2231.19   163.7 2214.69   205.8 2203.02
   217.2 2198.02   260.5 2183.57   330.4 2155.72   345.5 2148.19   358.7 2142.83
   394.1 2133.93   441.5 2128.32   456.7 2123.93   482.5 2124.19     491 2119.75
   509.4  2119.3   517.3 2119.96     531 2127.04   581.4 2163.42   627.3 2192.89
   653.4 2211.21     665 2217.66   699.2 2241.24   771.3 2288.88   804.1 2308.89
   820.4 2321.67     876 2352.22   901.7  2364.8   926.5 2381.75   949.3 2391.28
#Mann= 5 ,-1,0
       0      .1       0     491    .045       0   517.3      .1       0
     540     .06       0     680      .1       0
#XS Ineff= 2 , 0
          461.81 2128.46
Permanent Ineff=
       F       F
Bank Sta=491,517.3
XS Rating Curve= 0 ,0
Exp/Cntr=0.3,0.1

Type RM Length L Ch R = 1 ,2590    ,209.3,210.2,211.1
XS GIS Cut Line= 4
2207666.50972663406685.3084943932207938.72592865406962.969020453
2207995.89133108407106.3362201842208111.12952326407437.532599308
#Sta/Elev= 30
       0 2271.29    36.7 2255.76   139.5 2209.32   202.4 2184.55   248.1 2168.84
   305.2 2143.23   323.5 2137.72   380.1 2125.08   399.8    2122   412.8 2118.32
   425.5 2118.23   438.6 2120.23   460.1 2119.82   464.4 2119.35     473 2114.89
   483.62112.744   490.3 2112.19   496.3 2112.77   507.5 2118.01   516.1 2118.88
   524.7 2121.12   537.6  2127.9   541.9 2131.58   580.1 2170.96     597 2185.51
   677.5 2237.61   721.6 2267.82   763.1 2298.33   834.7 2348.27   893.9 2387.45
#Mann= 5 ,-1,0
       0      .1       0  438.84     .06       0   483.6    .045       0
   496.3     .06       0  623.18      .1       0
Bank Sta=483.6,496.3
XS Rating Curve= 0 ,0
Exp/Cntr(USF)=0,0
Exp/Cntr=0.3,0.1

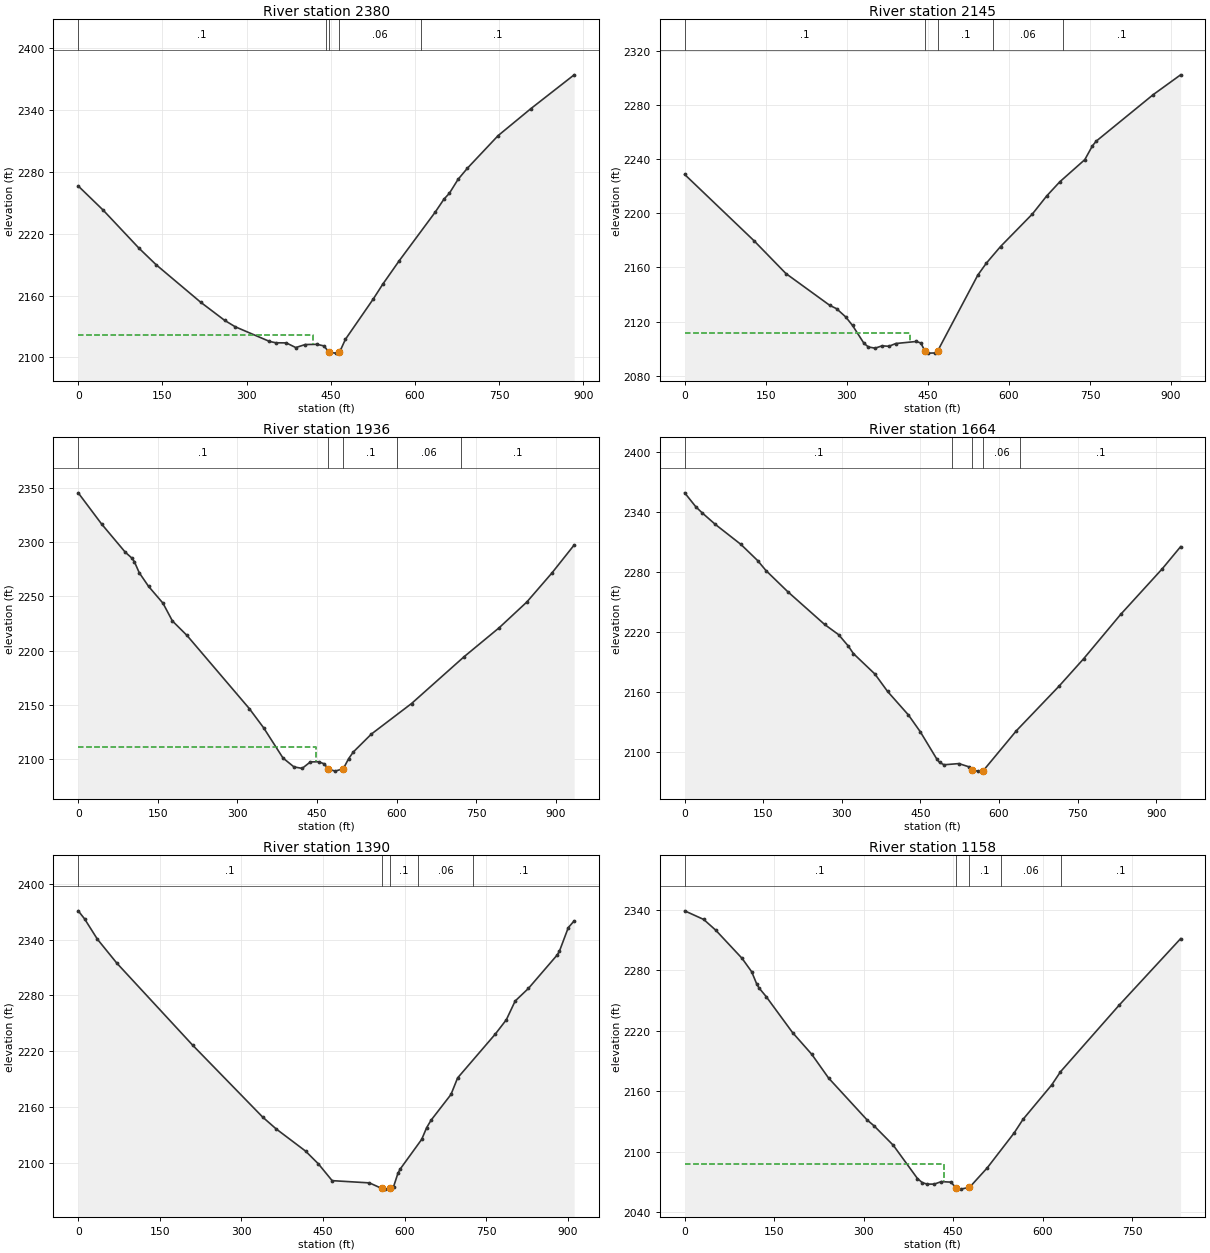
Type RM Length L Ch R = 1 ,2380    ,235.9,235.5,235.2
XS GIS Cut Line= 3
2207606.14729388406700.4276048192207749.51974234 407032.23241411
2207905.18125781 407530.62235399
#Sta/Elev= 30
       0 2266.22    44.4 2242.83   108.6 2205.72     139 2189.78   218.1 2153.55
   260.7 2136.01   279.7 2129.73   340.7 2115.54     352 2114.21   370.8 2114.08
   387.6 2109.56   404.4 2112.49   425.3  2112.7   437.9 2111.16     447 2104.88
   458.8 2104.17   464.3 2105.06   467.2 2106.98   476.1 2117.58   525.9 2156.82
   542.6 2170.98   571.6 2193.48   635.8 2240.66   651.7 2253.49   661.3 2259.15
   676.7 2272.58   693.2 2283.31     748 2314.97   806.6 2341.24   883.6 2373.97
#Mann= 5 ,-1,0
       0      .1       0  441.46     .06       0     447    .045       0
   464.3     .06       0  611.46      .1       0
#XS Ineff= 2 , 0
          418.59 2121.29
Permanent Ineff=
       F       F
Bank Sta=447,464.3
XS Rating Curve= 0 ,0
Exp/Cntr(USF)=0,0
Exp/Cntr=0.3,0.1

Type RM Length L Ch R = 1 ,2145    ,218.2,208.1,199
XS GIS Cut Line= 2
2207409.14910461406758.4344476942207698.21696232407629.419119556
#Sta/Elev= 30
       0 2228.62     128 2179.83   187.4 2155.49   268.4 2132.07   281.1 2129.56
   297.9 2123.52   310.6  2117.2   331.6 2104.11     340  2101.3   352.5 2100.46
   365.3 2102.18     378 2101.84   390.6 2103.88   428.5 2105.38     437 2104.27
   444.4 2098.46   450.7 2096.79   462.3  2096.9  468.382098.579   542.5 2154.41
   558.3 2163.21   584.5 2175.45   643.5 2199.49   669.9 2212.76   694.1 2223.18
   740.4 2239.54   754.5 2249.72   761.5 2253.18   866.9 2287.47   917.7 2302.12
#Mann= 5 ,-1,0
       0      .1       0   444.4    .045       0  468.38      .1       0
     570     .06       0     700      .1       0
#XS Ineff= 2 , 0
          417.66 2111.89
Permanent Ineff=
       F       F
Bank Sta=444.4,468.38
XS Rating Curve= 0 ,0
Exp/Cntr=0.3,0.1

Type RM Length L Ch R = 1 ,1936    ,270.1,272.3,274.6
XS GIS Cut Line= 4
2207132.33548802406906.6108402222207303.01697428407245.242908963
2207428.63854817407347.6518007192207637.55268735407680.822061899
#Sta/Elev= 30
       0  2345.2    44.1 2316.49    88.5 2290.66   101.4 2285.03   105.9 2281.77
     115 2271.67   132.6 2259.12   159.7 2243.66   177.5 2227.31   204.9 2214.01
   322.3 2146.73   349.4    2129   385.9 2101.19   406.5 2093.03     422 2091.67
   437.5 2097.62     453 2097.75   463.3  2095.9     471 2091.18   483.9 2089.14
   499.4 2091.31   509.7 2100.71   518.4 2106.76   552.5 2123.28   628.1 2151.34
   727.2 2194.44   793.3  2221.1   845.3 2244.73   892.5 2271.38   934.5 2297.18
#Mann= 5 ,-1,0
       0      .1       0     471    .045       0   499.4      .1       0
  601.29     .06       0  721.29      .1       0
#XS Ineff= 2 , 0
          447.89 2110.92
Permanent Ineff=
       F       F
Bank Sta=471,499.4
XS Rating Curve= 0 ,0
Exp/Cntr(USF)=0,0
Exp/Cntr=0.3,0.1

Type RM Length L Ch R = 1 ,1664    ,263.4,274.3,284
XS GIS Cut Line= 2
2206858.18508008 407112.562131262207483.18203146407823.502626291
#Sta/Elev= 30
       0  2359.5    21.2 2345.59    32.8 2339.75    58.5 2327.94   107.3 2307.95
   139.3 2291.77   155.3 2281.73   196.9 2260.62   267.1 2227.94   293.8 2217.72
     312 2206.55   322.1  2198.8     363 2178.43   387.3 2160.97   427.1 2137.44
   449.7 2120.71   480.8 2093.79   486.5 2089.99     495 2087.69   523.4 2088.86
   542.2 2085.69548.29582082.002     560 2081.33570.15282081.942   633.1 2121.68
   714.5 2166.24   761.4 2193.61   832.3 2238.06   911.6  2283.6   946.6  2305.7
#Mann= 5 ,-1,0
       0      .1       0     510     .06       0548.2958    .045       0
570.1528     .06       0     640      .1       0
Bank Sta=548.2958,570.1528
XS Rating Curve= 0 ,0
Exp/Cntr(USF)=0,0
Exp/Cntr=0.3,0.1

Type RM Length L Ch R = 1 ,1390    ,234.9,231.7,228.6
XS GIS Cut Line= 4
2206803.26158251407126.4485945252207014.90662547 407531.98780588
2206998.52120279407668.5329948892207055.87018218407979.856025828
#Sta/Elev= 30
       0 2370.94    11.6 2362.37    35.3 2340.37    71.1 2314.55   210.6 2226.16
   339.1 2148.87     364 2136.09   417.8 2112.33   441.5 2098.51   466.7 2080.49
   535.2 2078.08   558.1 2072.05   563.4 2071.36   572.5 2072.13   579.5 2073.83
   587.6 2088.37   591.6 2092.83   631.3 2124.93   640.4  2137.5   648.5 2145.54
   685.1 2173.24   697.3 2191.05   766.5 2238.22   786.8 2253.63   803.1 2273.86
   827.5 2287.45   880.3  2323.4   884.4 2327.43   900.7 2352.86   911.5  2360.1
#Mann= 5 ,-1,0
       0      .1       0   558.1    .045       0   572.5      .1       0
  624.97     .06       0  724.97      .1       0
Bank Sta=558.1,572.5
XS Rating Curve= 0 ,0
Exp/Cntr(USF)=0,0
Exp/Cntr=0.3,0.1

Type RM Length L Ch R = 1 ,1158    ,234.7,232.8,230.8
XS GIS Cut Line= 2
2206722.16420751407165.5042222722206811.18188632407991.857014259
#Sta/Elev= 30
       0 2339.29    31.9 2330.71      52 2320.09    96.2 2292.05   112.3 2278.72
   120.4 2267.07   124.4  2262.8   136.5 2254.13   180.7 2218.38   212.9 2196.77
   241.2  2173.1   305.4 2131.68   317.5 2125.56   349.7 2106.25   390.1 2073.28
     398 2069.29     406 2067.75   418.1 2067.73   430.1 2070.19   446.2  2069.7
   454.3 2064.27   462.3 2062.75   477.3 2064.48   506.9 2083.79     552 2118.48
   566.9 2132.02   615.1 2166.31   629.8 2179.38   727.9 2245.42   831.1 2311.65
#Mann= 5 ,-1,0
       0      .1       0   454.3    .045       0   477.3      .1       0
     530     .06       0     630      .1       0
#XS Ineff= 2 , 0
          434.93 2087.99
Permanent Ineff=
       F       F
Bank Sta=454.3,477.3
XS Rating Curve= 0 ,0
Exp/Cntr(USF)=0,0
Exp/Cntr=0.3,0.1

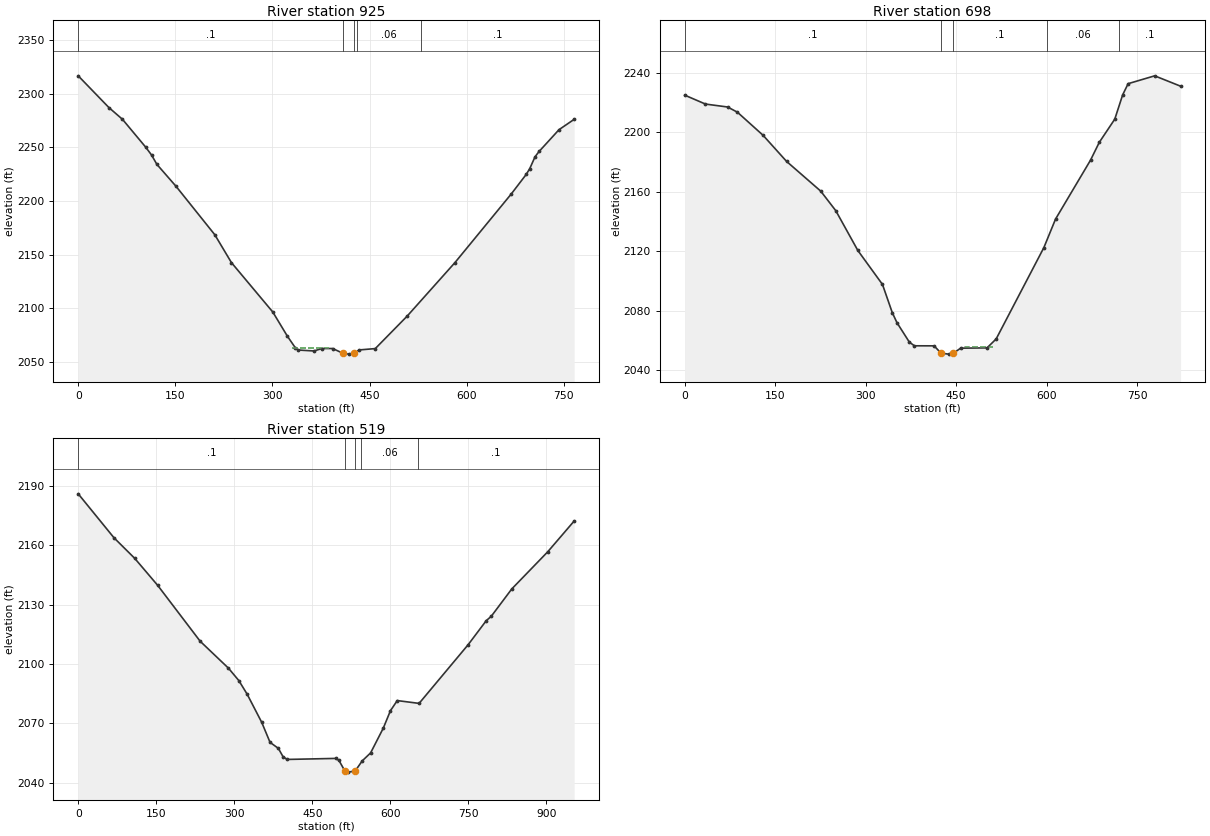
Type RM Length L Ch R = 1 ,925     ,232.6,227.3,221.2
XS GIS Cut Line= 2
2206447.85708626407275.0233228092206626.84973065408019.951898168
#Sta/Elev= 30
       0 2316.83    47.5 2287.16    68.4 2276.23   104.1 2250.36   113.3 2242.91
   121.5 2234.22   151.3 2213.58     211 2168.52   236.7 2142.51   300.6 2096.39
   323.1 2073.85   335.4 2063.02   339.6 2060.95   364.2 2060.04   376.6 2062.33
     393 2062.34   408.6    2058   417.7  2057.1   425.9 2058.03   434.2 2061.02
   458.9 2062.27   508.2 2092.61   581.9 2142.48   668.7 2206.38     692 2224.78
   697.5 2230.21   705.7 2241.32   711.9 2246.22   742.7 2266.57   766.1 2276.22
#Mann= 5 ,-1,0
       0      .1       0   408.6    .045       0   425.9      .1       0
     430     .06       0     530      .1       0
#XS Ineff= 1 ,-1
  329.55  385.45 2062.63
Permanent Ineff=
       F
Bank Sta=408.6,425.9
XS Rating Curve= 0 ,0
Exp/Cntr(USF)=0,0
Exp/Cntr=0.3,0.1

Type RM Length L Ch R = 1 ,698     ,176.8,178.6,181.3
XS GIS Cut Line= 4
2206233.86814435407335.362733708 2206308.9679983407724.516522382
2206389.52965982407831.0217698092206553.38388663408072.706754353
#Sta/Elev= 30
       0 2225.07    34.4 2219.07    71.1 2217.09    87.4 2213.59   129.9 2198.07
   168.9  2180.5   225.5 2160.52   250.4 2147.39     287 2120.61   327.8 2097.78
     344 2078.88   351.8 2072.08   372.3 2059.02   380.7 2056.53   413.4  2056.5
   424.8 2051.58   437.3 2050.93   444.8 2051.39   457.3 2054.93   501.1 2055.14
   516.2 2061.14   595.3 2122.58   614.6 2141.72   672.6 2181.36   687.1 2193.32
   712.8 2208.94   725.8 2225.19   734.9 2232.77   778.9 2238.05   821.9 2231.07
#Mann= 5 ,-1,0
       0      .1       0   424.8    .045       0   444.8      .1       0
  599.88     .06       0  719.88      .1       0
#XS Ineff= 1 ,-1
  464.67  510.94 2055.97
Permanent Ineff=
       F
Bank Sta=424.8,444.8
XS Rating Curve= 0 ,0
Exp/Cntr(USF)=0,0
Exp/Cntr=0.3,0.1

Type RM Length L Ch R = 1 ,519     ,94,96.2,98.1
BEGIN DESCRIPTION:
structure xs 4
END DESCRIPTION:
XS GIS Cut Line= 4
 2206128.5931683407364.591888635 2206138.3627508407758.166498052
2206258.38905013  407988.44951422206501.23295807408164.301999259
#Sta/Elev= 30
       0 2185.92    68.6 2163.76   108.6 2153.32   152.6 2139.72   234.4 2111.44
   288.7 2097.85   308.7 2091.57   324.7 2084.69   352.7 2070.47   368.7 2060.36
   384.7 2057.31   393.7 2053.09   401.6 2051.72   495.1 2052.24   501.1 2051.24
   512.9 2045.72   518.9 2045.31   532.4 2045.91   545.9    2051     562 2055.03
   586.5 2067.61   600.1 2076.34   613.2 2081.46   655.2 2080.04   749.4 2109.67
   784.2 2121.82   793.9 2124.05   833.4 2137.89   902.5 2156.65   953.2 2172.18
#Mann= 5 ,-1,0
       0      .1       0   512.9    .045       0   532.4      .1       0
   543.7     .06       0  653.38      .1       0
Bank Sta=512.9,532.4
XS Rating Curve= 0 ,0
Exp/Cntr(USF)=0,0
Exp/Cntr=0.5,0.3