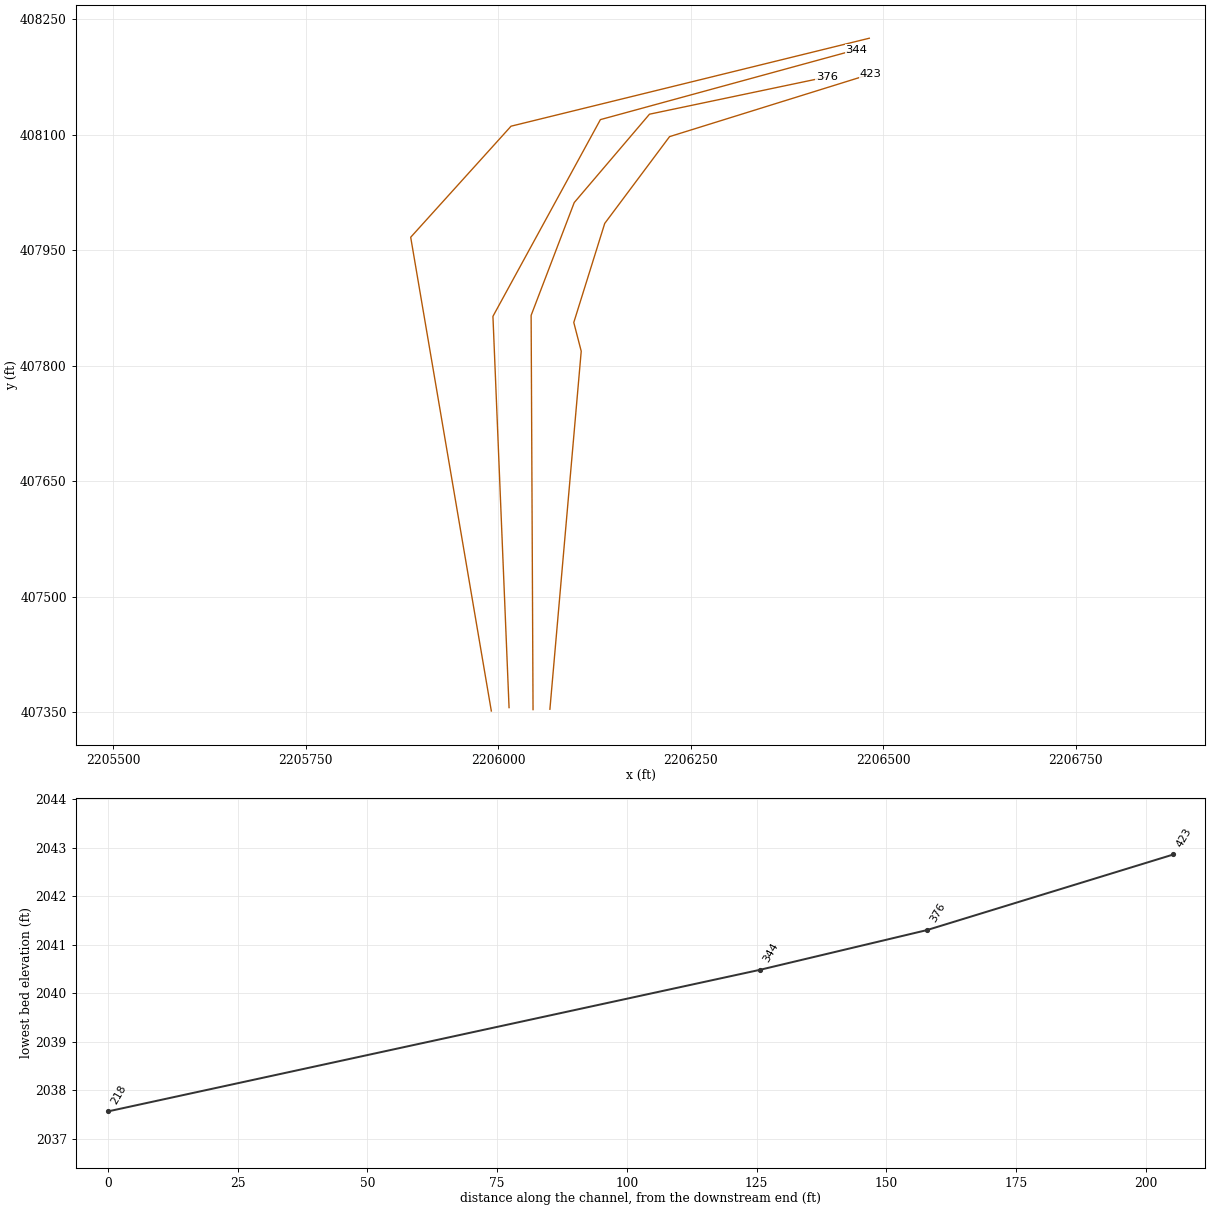
HEC-RAS study ISLNDLCKRN.prj: ISLNDLCKRN

--- ISLNDLCKRN.g01 (geometry) --- (continued)

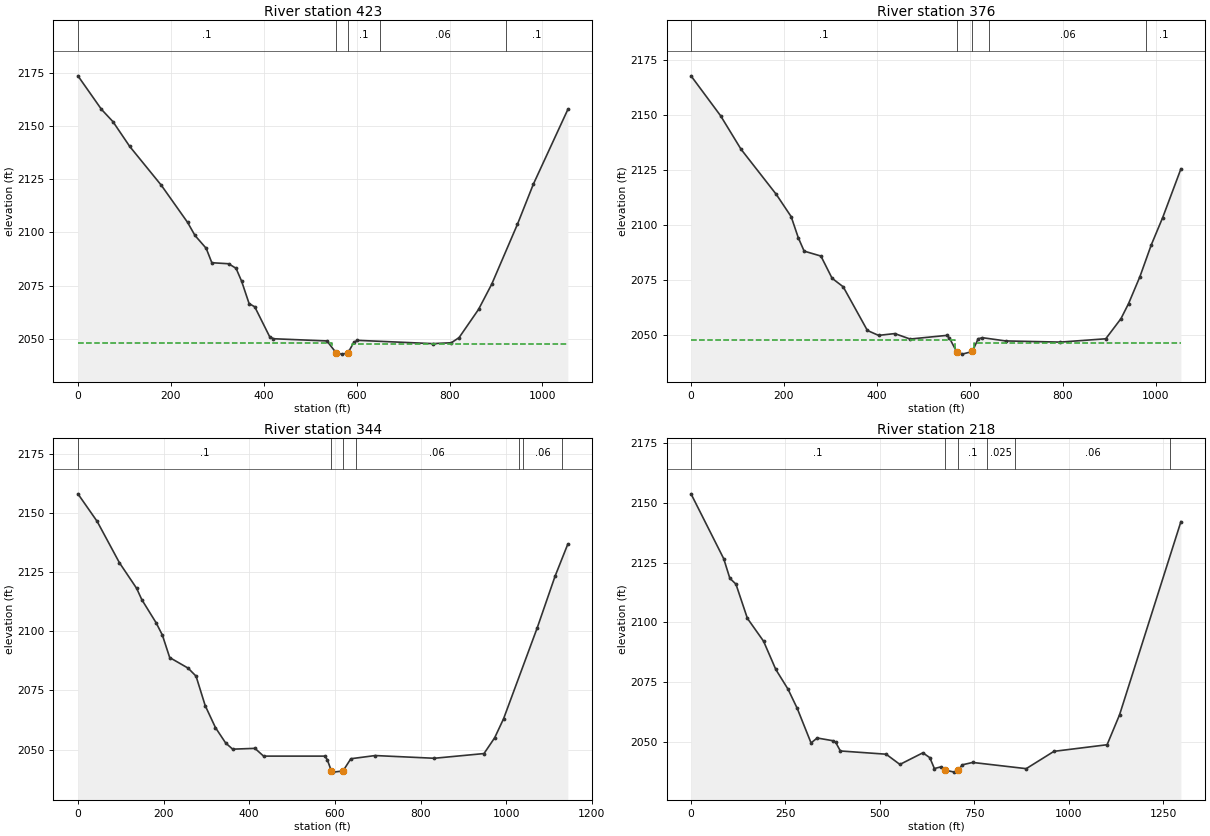
Type RM Length L Ch R = 1 ,423     ,47.4,47.5,47.7
BEGIN DESCRIPTION:
structure xs 3; 8.5 ft between structure & xs
END DESCRIPTION:
XS GIS Cut Line= 6
2206067.19349396407354.1140908362206107.86563263407818.985959996
2206098.20448527407856.2606676422206138.39640782407984.881343765
 2206222.6200812408097.5642671332206483.72904765408178.787303977
#Sta/Elev= 30
       0 2173.54    50.7 2157.79    75.4 2152.03   111.5 2140.39   179.7  2122.1
     236 2104.75     252 2098.58   276.1 2092.55   288.3 2085.78   324.3  2085.3
   340.4 2083.17   352.4 2077.09   368.5  2066.6   380.7 2065.07   412.6 2051.12
   420.7 2050.09     536 2049.05   556.3 2043.37   568.2 2042.86   581.1 2043.39
   593.9 2048.35   601.7 2049.34   763.7 2047.79   803.8  2048.2   820.5 2050.61
   862.4 2063.86   890.8 2075.72   946.2 2103.86   980.2 2122.57  1054.6 2157.74
#Mann= 5 ,-1,0
       0      .1       0   556.3    .045       0   581.1      .1       0
   650.5     .06       0  921.18      .1       0
#XS Ineff= 2 , 0
           547.8 2047.92  589.69         2047.75
Permanent Ineff=
       F       F
Bank Sta=556.3,581.1
XS Rating Curve= 0 ,0
Exp/Cntr(USF)=0,0
Exp/Cntr=0.5,0.3

Type RM Length L Ch R = 1 ,376     ,35.4,32.2,30.7
BEGIN DESCRIPTION:
structure xs 2; 14.7 ft between structure and xs
END DESCRIPTION:
XS GIS Cut Line= 5
2206045.29393278407353.6170529682206042.81361599407865.482890076
2206098.76792491408011.906319002 2206196.5288822408126.681071754
2206426.55833071408174.931108418
#Sta/Elev= 30
       0 2167.75    63.6 2149.63   107.6 2134.41   183.6 2113.86   215.6 2103.76
   230.9 2094.17   243.5  2088.1   279.6 2085.86   303.6 2075.78   327.6 2071.88
   379.6 2052.05   403.6 2049.82   438.6 2050.63   471.6 2048.16   550.1 2049.81
   556.1 2048.67   571.7 2042.38   583.9  2041.3   605.6 2042.51     618 2048.26
   627.2 2048.77     677  2047.3   794.2 2046.76   892.6 2048.27   925.3  2057.4
   941.6 2064.21   966.2 2076.53   990.7    2091  1015.2 2103.37  1054.4 2125.49
#Mann= 5 ,-1,0
       0      .1       0   571.7    .045       0   605.6      .1       0
  641.87     .06       0  979.39      .1       0
#XS Ineff= 2 , 0
           568.7 2047.92   608.6          2046.2
Permanent Ineff=
       F       F
Bank Sta=571.7,605.6
XS Rating Curve= 0 ,0
Exp/Cntr(USF)=0,0
Exp/Cntr=0.5,0.3

Type RM Length L Ch R = 1 ,344     ,132.4,125.6,123.3
BEGIN DESCRIPTION:
structure xs 1
END DESCRIPTION:
XS GIS Cut Line= 4
2206014.14948755407356.217960775 2205993.2146679407864.236250944
2206132.78013223408119.6410506732206464.94593734408210.358602488
#Sta/Elev= 30
       0 2158.15      45 2146.47      97 2128.99   137.1 2118.19   149.1 2113.43
   182.7 2103.59   197.1 2098.46   214.3 2088.92   257.2 2084.46   275.8 2081.07
   297.2 2068.59   321.2 2059.28     345 2052.79   361.3 2050.19   413.3 2050.53
   433.5 2047.25   576.2 2047.25   582.1  2045.8   591.6 2041.06   596.1 2040.48
   618.9 2040.97   637.2 2046.14   694.1 2047.49     832 2046.34   948.1 2048.33
     973 2055.01   993.8 2063.05  1072.5 2101.56    1114 2123.31  1143.8 2136.91
#Mann= 7 ,-1,0
       0      .1       0   591.6    .045       0   618.9      .1       0
  648.45     .06       0  1029.5      .1       0  1039.5     .06       0
  1129.5      .1       0
Bank Sta=591.6,618.9
XS Rating Curve= 0 ,0
Exp/Cntr(USF)=0,0
Exp/Cntr=0.3,0.1

Type RM Length L Ch R = 1 ,218     ,,,
XS GIS Cut Line= 4
2205991.11628676 407351.829693382205886.40758529407966.905851432
 2206016.7410924408111.1071122892206481.98443261408225.318473783
#Sta/Elev= 30
       0 2153.66    86.6  2126.6   102.8 2118.45     119 2115.98   149.3 2101.72
   192.1 2092.19   224.5 2080.41     257 2072.15   281.3 2064.15   317.9 2049.73
   334.1  2051.8   374.7 2050.69   382.8 2050.09   395.5 2046.39   516.7 2045.04
   553.2 2040.77   614.1 2045.62   632.4 2043.59   644.5 2039.06   660.8 2039.71
672.42612038.414   697.6 2037.56   707.9 2038.48   718.6 2040.61   745.9  2041.6
   887.7 2039.01   961.2 2046.23  1101.9 2048.99  1134.9 2061.48  1297.4 2142.07
#Mann= 6 ,-1,0
       0      .1       0672.4261    .045       0   707.9      .1       0
  783.93    .025       0   858.3     .06       0  1268.3      .1       0
Bank Sta=672.4261,707.9
XS Rating Curve= 0 ,0
Exp/Cntr(USF)=0,0
Exp/Cntr=0.3,0.1
LCMann Table=0

Chan Stop Cuts=-1
Use User Specified Reach Order=0
Composite Channel Slope=5